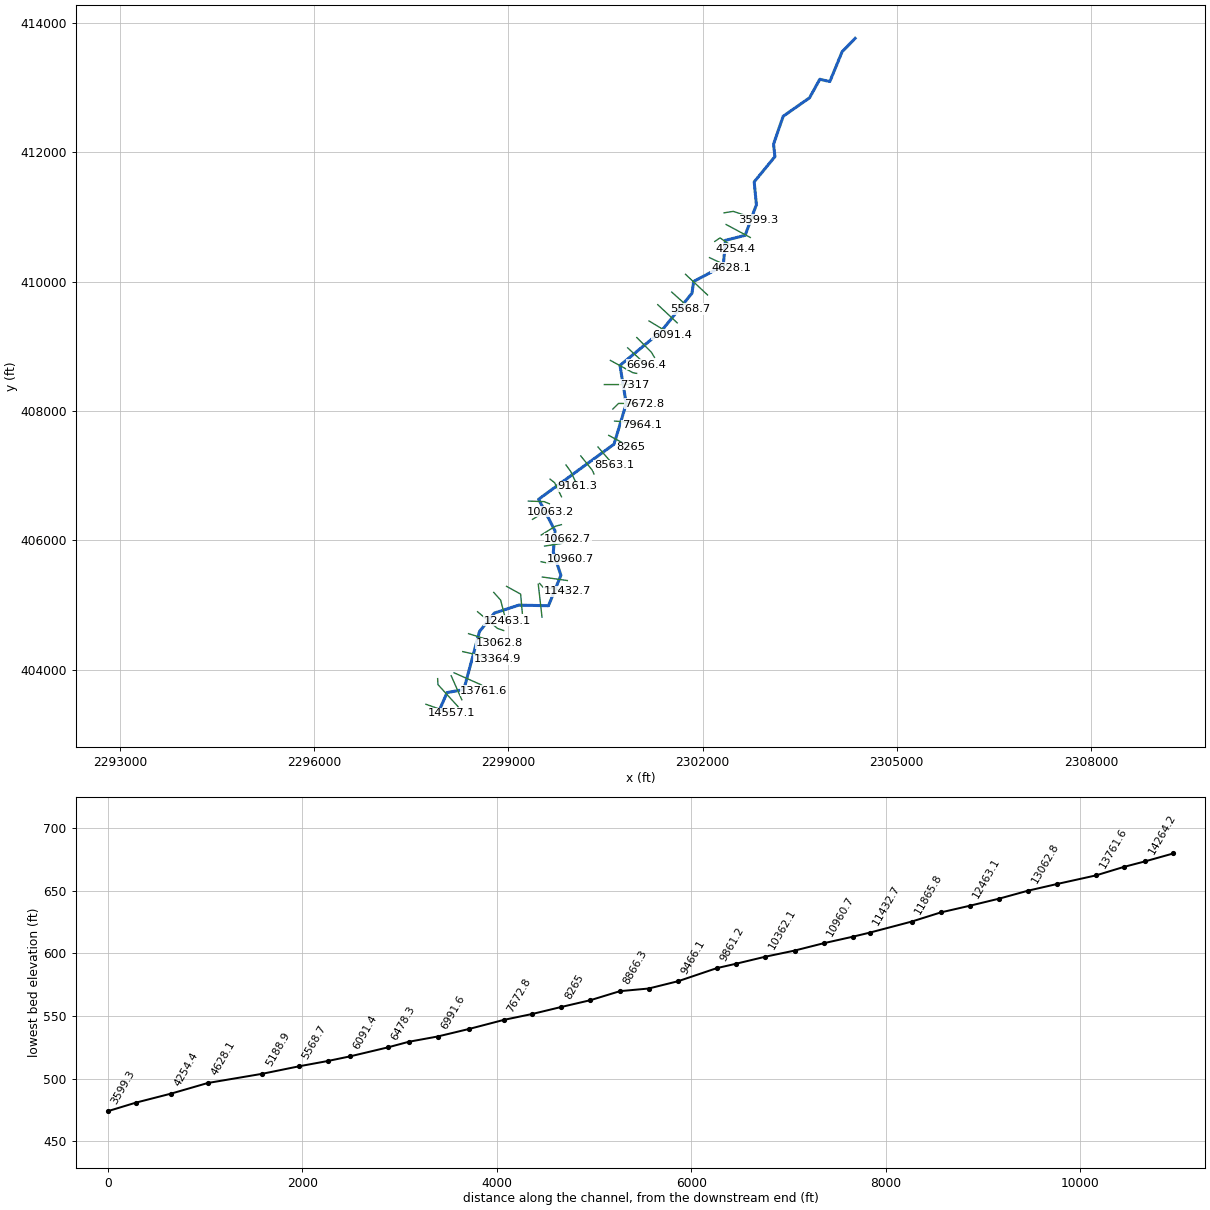
--- WILLETRUN.prj (project) ---

Proj Title=WILLETRUN
Current Plan=p01
Default Exp/Contr=0,0
English Units
Geom File=g01
Flow File=f01
Plan File=p01
BEGIN DESCRIPTION:
END DESCRIPTION:
DSS Export Rating Curves= 0
DSS Export Rating Curve Sorted= 0
DSS Export Volume Flow Curves= 0
DXF OffsetX= 0
DXF OffsetY= 0
DXF ScaleX= 0
DXF ScaleY= 0

--- WILLETRUN.p01 (plan) ---

Plan Title=Floodplain
Program Version=4.00
Geom File=g01
Flow File=f01
K Sum by GR=0
Std Step Tol=0.01
Critical Tol=0.01
Num of Std Step Trials=20
Max Error Tol=0.3
Flow Tol Ratio=0.001
Split Flow NTrial=30
Split Flow Tol=0.02
Split Flow Ratio=0.02
Log Output Level=0
Friction Slope Method=1
Unsteady Friction Slope Method=2
Unsteady Bridges Friction Slope Method=1
Global Log Level=0
CheckData=False
Run HTab=0
Run UNet=0
Run PostProcess=0
UNET Theta=0
UNET Theta Warmup=0
UNET ZTol=0
UNET ZSATol=0
UNET MxIter=0
UNET MaxInSteps=0
UNET DtIC=0
UNET DtMin=0
UNET MaxCRTS=0
UNET WFStab=0
UNET SFStab=0
UNET WFX=0
UNET SFX=0
UNET DSS MLevel=0
UNET DZMax Abort=0
UNET Convert EG Bridges=0
UNET Use Existing IB Tables=0
UNET Froude Limit=0
UNET Froude Power=0
Write IC File=0
Echo Input=False
Echo Output=False
Write Detailed=0

--- WILLETRUN.f01 (steady flow) ---

Flow Title=NFF Regression Equation
Program Version=4.00
Number of Profiles=1
Profile Names=P100yr
River Rch & RM=WILLETRUN,Main      ,14557.1
417.7506
River Rch & RM=WILLETRUN,Main      ,14264.2
417.9293
River Rch & RM=WILLETRUN,Main      ,14046.1
568.4033
River Rch & RM=WILLETRUN,Main      ,12163.3
593.5844
River Rch & RM=WILLETRUN,Main      ,11865.8
807.0411
River Rch & RM=WILLETRUN,Main      ,8265
840.8877
River Rch & RM=WILLETRUN,Main      ,6991.6
930.7304
River Rch & RM=WILLETRUN,Main      ,4254.4
965.8018
River Rch & RM=WILLETRUN,Main      ,3888.7
1070.224
River Rch & RM=WILLETRUN,Main      ,1126.7
1094.556
River Rch & RM=WILLETRUN,Main      ,741.3
1123.483
Boundary for River Rch & Prof#=WILLETRUN,Main      ,1
Up Type=0
Dn Type=3
Dn Slope=0.015598

--- WILLETRUN.g01 (geometry) ---

Geom Title=USGS 10m DEM
Program Version=4.10

River Reach=WILLETRUN       ,Main
Reach XY= 30
     2297936.095      403382.402     2298053.985      403650.906
     2298312.576      403697.407     2298554.492      404595.699
     2298785.754      404879.723     2299160.184      405001.352
     2299619.846      404992.009     2299811.617      405462.234
       2299694.8      405818.484     2299722.057      406147.863
     2299467.683      406637.189     2300632.915      407488.258
     2300820.941      408114.049     2300724.419      408704.108
     2301359.272      409230.058     2301836.467      409820.122
     2301862.998      410001.524     2302320.465       410244.52
     2302353.151      410636.715     2302658.459      410714.022
     2302831.405      411187.309     2302797.529      411539.576
     2303117.579      411929.977     2303096.826      412122.594
     2303245.414      412553.433     2303653.033      412838.701
     2303810.532      413124.458       2303966.1      413089.436
     2304155.964        413550.1     2304357.191      413756.841

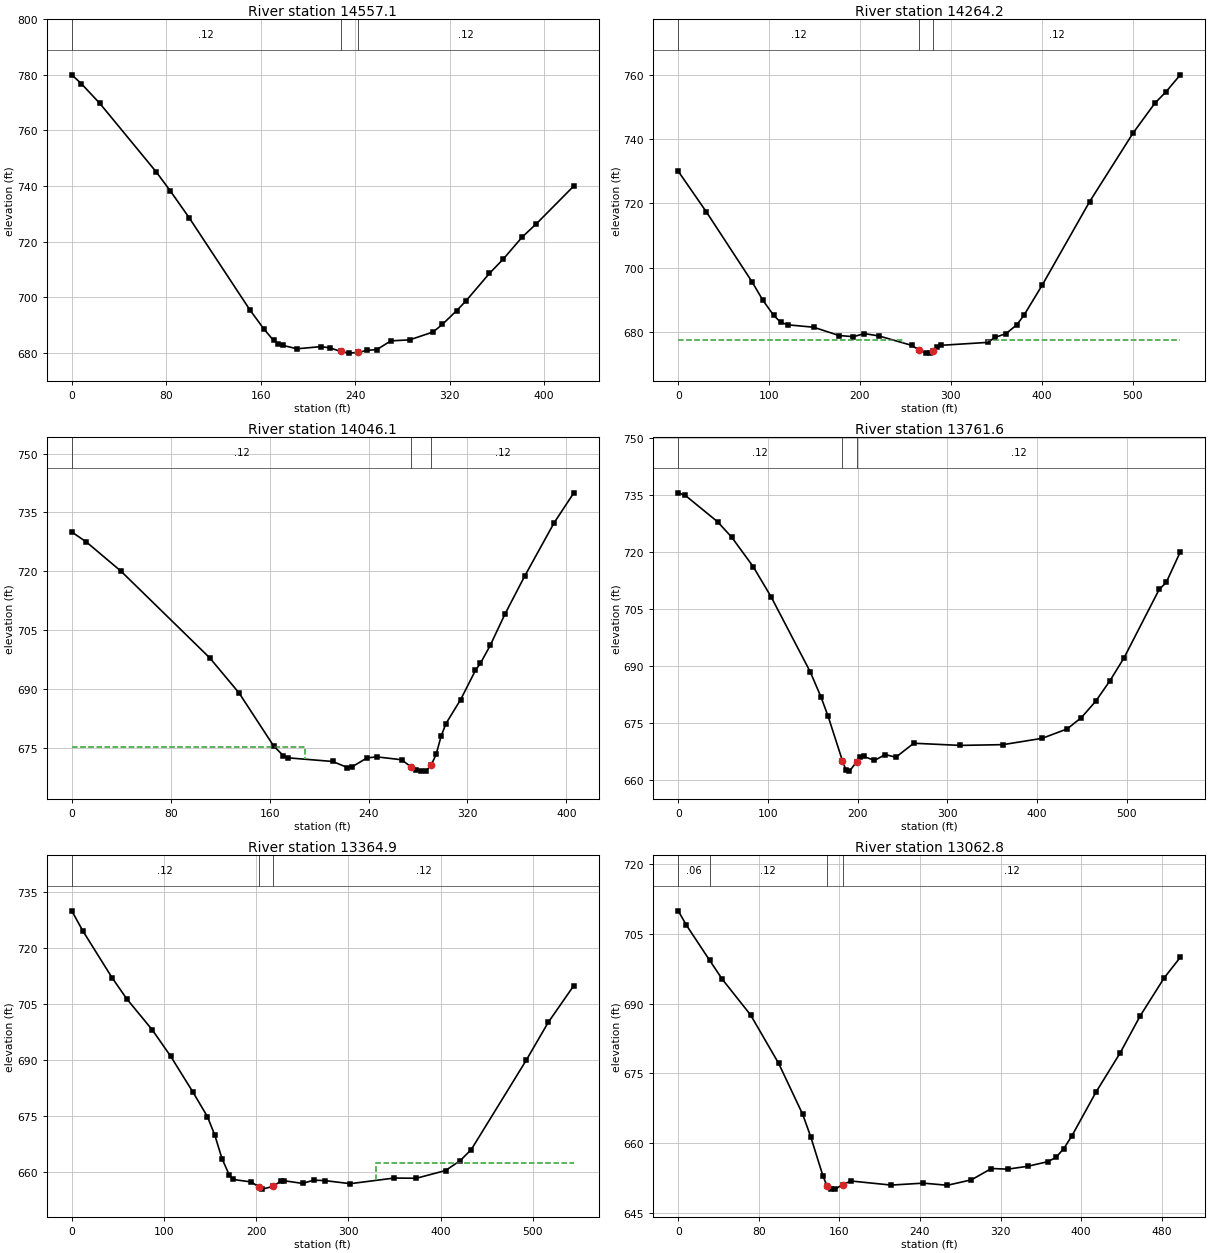
Type RM Length L Ch R = 1 ,14557.1 ,300.2,292.9,279.4
XS GIS Cut Line= 2
     2297726.697      403469.955     2298128.114      403329.353
#Sta/Elev= 30
       0     780       8  776.86    23.8   769.7    71.6  745.02    83.5   738.2
    99.4  728.58     151  695.31     163  688.36   170.9   684.4   174.9  683.26
   178.9   682.6   190.8  681.38   210.7  682.14   218.6  681.75   227.7  680.43
   234.5  679.82   242.7  680.08   250.4  680.84   258.4  681.09   270.3  684.24
   286.2  684.59   306.1  687.44     314  690.18     326  695.11   333.9  698.61
   353.8  708.52   365.7  713.76   381.6  721.63   393.5  726.35   425.3     740
#Mann= 3 ,-1 , 0
       0     .12       0   227.7    .045       0   242.7     .12       0
Bank Sta=227.7,242.7
XS Rating Curve= 0 ,0
Exp/Cntr=0.3,0.1

Type RM Length L Ch R = 1 ,14264.2 ,223.6,218,210.2
XS GIS Cut Line= 3
     2297907.736      403866.229     2297913.015      403773.439
     2298222.612      403433.833
#Sta/Elev= 30
       0     730      31  717.34    81.3  695.58    92.9  689.99   104.9  685.22
   112.9  682.99   120.9  682.23   148.9   681.5   176.9  678.92   192.8  678.55
   204.8  679.51   220.8  678.79   256.8  675.86   264.8  674.47   272.6  673.46
   276.8  673.44   280.8  674.23   284.8  675.44   288.8  675.86   340.7  676.78
   348.7  678.34   360.7  679.51   372.7  682.28   380.7  685.34   400.6  694.62
   452.6   720.5   500.5  741.87   524.5  751.16   536.5  754.62   552.5  759.98
#Mann= 3 ,-1 , 0
       0     .12       0   264.8    .045       0   280.8     .12       0
#XS Ineff= 2 , 0
           246.9  677.58  340.13          677.64
Permanent Ineff=
       F       F
Bank Sta=264.8,280.8
XS Rating Curve= 0 ,0
Exp/Cntr=0.3,0.1

Type RM Length L Ch R = 1 ,14046.1 ,266.7,284.5,300.7
XS GIS Cut Line= 2
     2298116.783      403910.639     2298281.241       403539.41
#Sta/Elev= 30
       0     730    11.9  727.42    39.8     720   111.5  697.92   135.3  688.94
   163.2  675.45   171.2  672.92   175.2   672.4     211  671.48   222.9  669.94
   226.9  670.16   238.8   672.4   246.8  672.65   266.7  671.92   274.7  670.02
   278.6  669.21   282.6  669.02   286.6  669.14   290.6  670.53   294.6  673.26
   298.6  677.85   302.5   681.1   314.5  687.28   326.4  694.69   330.4  696.48
   338.4  701.09   350.3  709.06   366.2  718.71   390.1  732.36     406  739.98
#Mann= 3 ,-1 , 0
       0     .12       0   274.7    .045       0   290.6     .12       0
#XS Ineff= 2 , 0
          188.75  675.08
Permanent Ineff=
       F       F
Bank Sta=274.7,290.6
XS Rating Curve= 0 ,0
Exp/Cntr=0.3,0.1

Type RM Length L Ch R = 1 ,13761.6 ,392,396.7,401
XS GIS Cut Line= 3
      2298161.08      403956.142     2298586.812      403767.593
     2298621.066      403679.585
#Sta/Elev= 30
       0  735.53       8  734.83    43.8  727.93    59.7  723.84    83.6   716.1
   103.5   708.2   147.2  688.43   159.2  681.81   167.1  676.77   183.1  665.05
     187  662.61     191  662.29     199  664.75     203  665.94   206.9  666.18
   218.9  665.09   230.8  666.64   242.8  665.96   262.7  669.63   314.4  669.06
   362.2  669.26   405.9  670.92   433.8   673.4   449.7  676.39   465.6  680.67
   481.4  686.03   497.1  692.05   536.4  710.09   544.3  711.95     560     720
#Mann= 3 ,-1 , 0
       0     .12       0   183.1    .045       0     199     .12       0
Bank Sta=183.1,199
XS Rating Curve= 0 ,0
Exp/Cntr=0.3,0.1

Type RM Length L Ch R = 1 ,13364.9 ,302.7,302,298.8
XS GIS Cut Line= 2
     2298295.541      404283.704     2298826.649      404164.537
#Sta/Elev= 30
       0  730.01    11.9  724.67    43.7  712.09    59.6  706.44    87.4  698.09
   107.3  691.03   131.1  681.56     147  674.93     155  669.98   162.9  663.62
   170.8  659.24   174.8  658.07   194.7  657.39   202.6   656.1   206.6  655.48
   218.5  656.23   226.5  657.62   230.4  657.72   250.3  657.01   262.2  657.88
   274.1  657.77     302  656.94   349.6  658.45   373.5  658.39   405.2  660.46
   421.2  663.13   433.1  666.08   492.7     690   516.5  700.12   544.3     710
#Mann= 3 ,-1 , 0
       0     .12       0   202.6    .045       0   218.5     .12       0
#XS Ineff= 2 , 0
                          329.98          662.36
Permanent Ineff=
       F       F
Bank Sta=202.6,218.5
XS Rating Curve= 0 ,0
Exp/Cntr=0.3,0.1

Type RM Length L Ch R = 1 ,13062.8 ,307.6,298.9,289.6
XS GIS Cut Line= 2
     2298385.281      404560.794     2298861.207      404412.537
#Sta/Elev= 30
       0     710       8  706.95   31.12699.3671    43.9  695.22    71.8   687.6
    99.7  677.16   123.6  666.18   131.6  661.32   143.6  652.98   147.6  650.84
   151.5  650.13   155.5  650.09   163.7  651.08   171.5  651.84   211.4  650.96
   243.3  651.38   267.2  650.92   291.1  652.09     311  654.53     327  654.39
   346.9     655   366.9     656   374.9   656.9   382.8  658.81   390.8  661.54
   414.7  670.94   438.7  679.38   458.6  687.36   482.5  695.57   498.5     700
#Mann= 4 ,-1 , 0
       0     .06       0   31.12     .12       0   147.6    .045       0
   163.7     .12       0
Bank Sta=147.6,163.7
XS Rating Curve= 0 ,0
Exp/Cntr=0.3,0.1

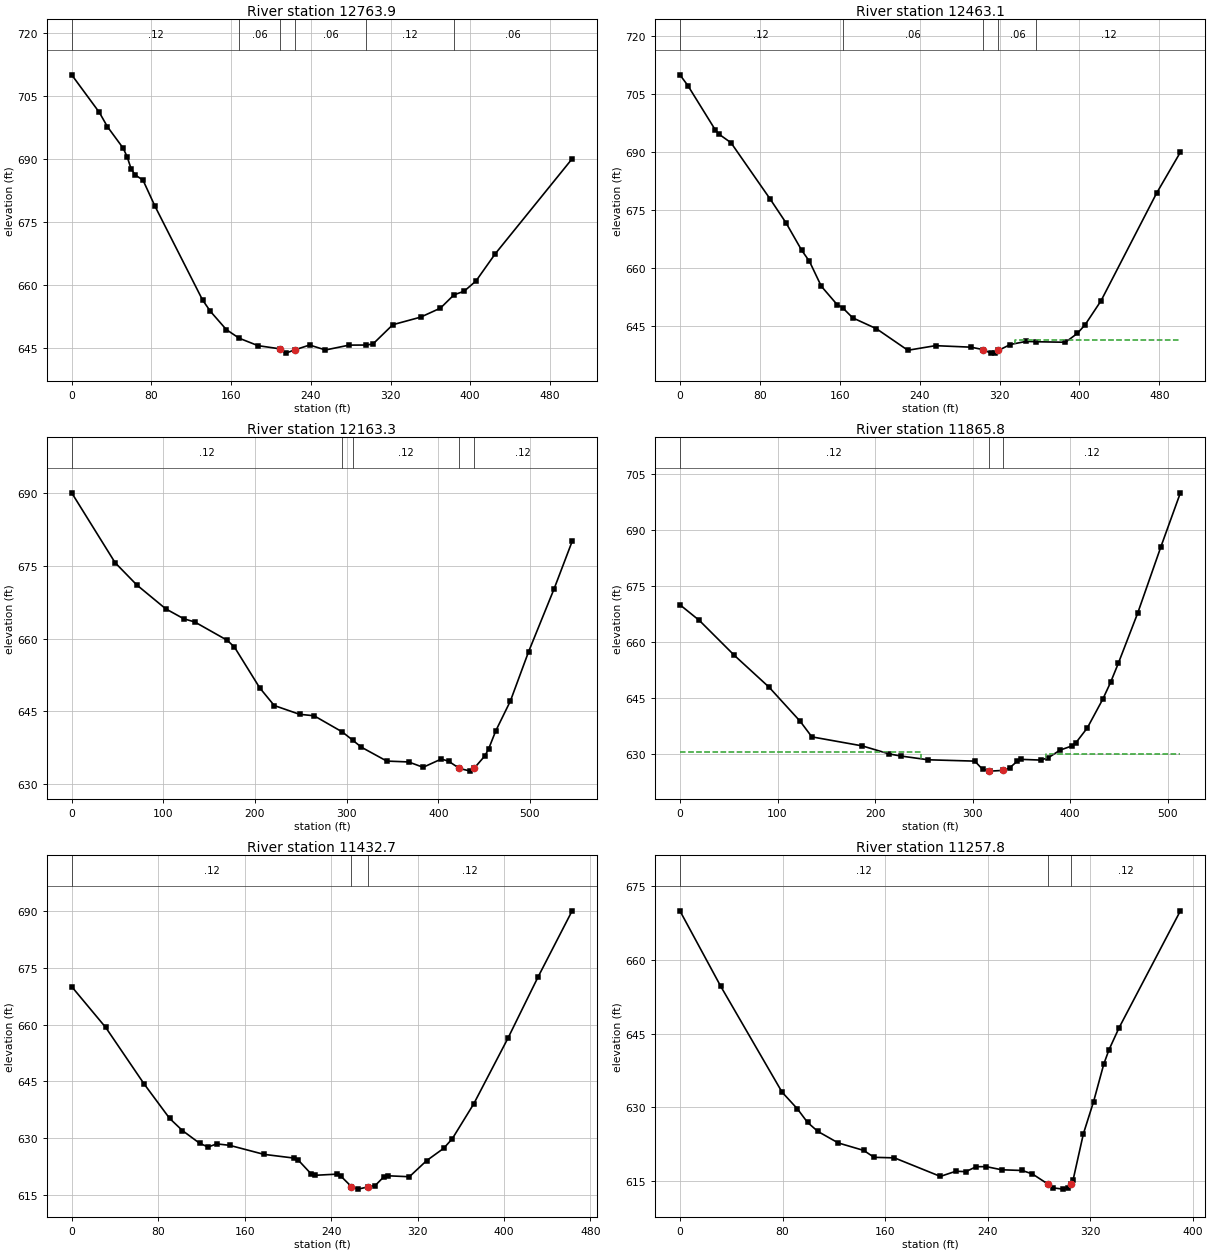
Type RM Length L Ch R = 1 ,12763.9 ,314.7,300.8,286.4
XS GIS Cut Line= 3
     2298524.411      404899.285     2298832.565      404641.299
     2298927.611       404609.04
#Sta/Elev= 30
       0     710    27.8  701.03    35.8  697.66    51.7  692.52    55.7  690.45
    59.7  687.56    63.7  686.16    71.6   684.9    83.6   678.7   131.3  656.38
   139.3  653.63   155.2  649.31  168.07 647.256     187  645.48   209.1  644.72
   214.9   643.7   224.1  644.49   238.8  645.63   254.7  644.45   278.5  645.61
  295.48645.6254   302.4  645.88   322.3  650.47   350.2  652.27   370.1  654.42
  383.67 657.579   393.9  658.45   405.8  660.89     425  667.33   502.3     690
#Mann= 6 ,-1 , 0
       0     .12       0  168.07     .06       0   209.1    .045       0
   224.1     .06       0  295.48     .12       0  383.67     .06       0
Bank Sta=209.1,224.1
XS Rating Curve= 0 ,0
Exp/Cntr=0.3,0.1

Type RM Length L Ch R = 1 ,12463.1 ,302.7,299.8,295.3
XS GIS Cut Line= 4
     2298774.295      405198.356     2298881.389       405077.88
     2298945.115      404829.538     2298988.847      404758.397
#Sta/Elev= 30
       0     710     7.9  707.23    35.4  695.76    39.3  694.62    51.1  692.45
    90.4  677.86   106.2  671.74   121.9  664.64   129.7  661.77   141.5  655.36
   157.3  650.62  162.99649.7592     173  647.17   196.7  644.37   228.2  638.79
   255.9  639.98   291.4  639.59   303.8  638.95   311.1  638.05     315  638.07
   318.8  638.74   330.8  640.28   346.6  641.08  356.89640.9935     386  640.86
   397.9  643.14   405.8  645.42   421.6  651.57   477.2  679.37   501.1     690
#Mann= 5 ,-1 , 0
       0     .12       0  162.99     .06       0   303.8    .045       0
   318.8     .06       0  356.89     .12       0
#XS Ineff= 2 , 0
                          335.78           641.4
Permanent Ineff=
       F       F
Bank Sta=303.8,318.8
XS Rating Curve= 0 ,0
Exp/Cntr=0.3,0.1

Type RM Length L Ch R = 1 ,12163.3 ,296.9,297.5,297.5
XS GIS Cut Line= 3
     2298972.114      405291.636     2299189.887      405171.702
     2299215.889      404875.346
#Sta/Elev= 30
       0     690    47.4  675.61      71  671.04   102.6  666.12   122.3  664.07
   134.2  663.42   169.7  659.64   177.6  658.24   205.2  649.84     221  646.21
   248.6   644.4   264.5   644.1  295.35640.7612  307.01639.0181     316  637.64
   343.8  634.77   367.6  634.59   383.5  633.49   403.3  635.19   411.2  634.75
   423.1  633.26     435   632.7     439  633.25   450.9  635.85   454.9  637.25
   462.8  641.01   478.7  647.13   498.5  657.25   526.3  670.18   546.1     680
#Mann= 5 ,-1 , 0
       0     .12       0  295.35     .06       0  307.01     .12       0
   423.1    .045       0     439     .12       0
Bank Sta=423.1,439
XS Rating Curve= 0 ,0
Exp/Cntr=0.3,0.1

Type RM Length L Ch R = 1 ,11865.8 ,398.6,433.1,463.2
XS GIS Cut Line= 2
     2299461.899      405324.828     2299520.114      404815.266
#Sta/Elev= 30
       0     670    19.9   665.8    55.7  656.46    91.4   647.9   123.2  638.78
   135.2   634.6   186.9  632.18   214.7  630.01   226.6  629.46   254.4  628.46
   302.2   628.1   310.1  625.91   316.3   625.5   318.1  625.42   331.3  625.62
   337.9  626.29   345.9  628.12   349.9  628.57   369.8  628.38   377.7  629.04
   389.6  631.05   401.6  632.16   405.5  632.92   417.5     637   433.4  644.72
   441.3  649.18   449.3  654.32   469.1  667.74     493  685.61   512.9     700
#Mann= 3 ,-1 , 0
       0     .12       0   316.3    .045       0   331.3     .12       0
#XS Ineff= 2 , 0
          246.58   630.6  374.79           629.9
Permanent Ineff=
       F       F
Bank Sta=316.3,331.3
XS Rating Curve= 0 ,0
Exp/Cntr=0.3,0.1

Type RM Length L Ch R = 1 ,11432.7 ,175.6,174.9,174.3
XS GIS Cut Line= 3
     2299484.114      405336.777     2299535.479      405277.172
     2299915.239      405217.413
#Sta/Elev= 30
       0     670    31.5  659.22    66.9  644.36    90.6  635.23   102.5  632.01
   118.3  628.68   126.2  627.67   134.2   628.5   146.1  628.12   177.8  625.74
   205.5  624.76   209.5  624.27   221.4  620.63   225.3  620.21   245.1  620.51
   249.1  619.98   258.8  617.24     265  616.56   273.8  617.12   280.8   617.5
   288.7  619.76   292.7  620.08   312.5  619.83   328.4  624.07   344.2  627.32
   352.2  629.86     372  639.04   403.7  656.39   431.4  672.46   463.1     690
#Mann= 3 ,-1 , 0
       0     .12       0   258.8    .045       0   273.8     .12       0
Bank Sta=258.8,273.8
XS Rating Curve= 0 ,0
Exp/Cntr=0.3,0.1

Type RM Length L Ch R = 1 ,11257.8 ,290.1,297.1,303.1
XS GIS Cut Line= 2
     2299524.972      405435.679     2299911.283      405381.368
#Sta/Elev= 30
       0  669.99    31.8  654.62    79.6  633.06    91.6  629.64    99.5  626.88
   107.5  625.06   123.4  622.71   143.3  621.18   151.3  619.78   167.2  619.67
     203  615.89     215  616.94   222.9  616.86   230.9  617.87   238.8  617.88
   250.8  617.24   266.7   617.1   274.7   616.4   286.6  614.37   290.6  613.57
   298.6   613.3   302.5  613.58  304.56   614.4   306.5  615.22   314.5  624.59
   322.4   631.1   330.4  638.79   334.4  641.67   342.3  646.18   390.1     670
#Mann= 3 ,-1 , 0
       0     .12       0   286.6    .045       0  304.56     .12       0
Bank Sta=286.6,304.56
XS Rating Curve= 0 ,0
Exp/Cntr=0.3,0.1

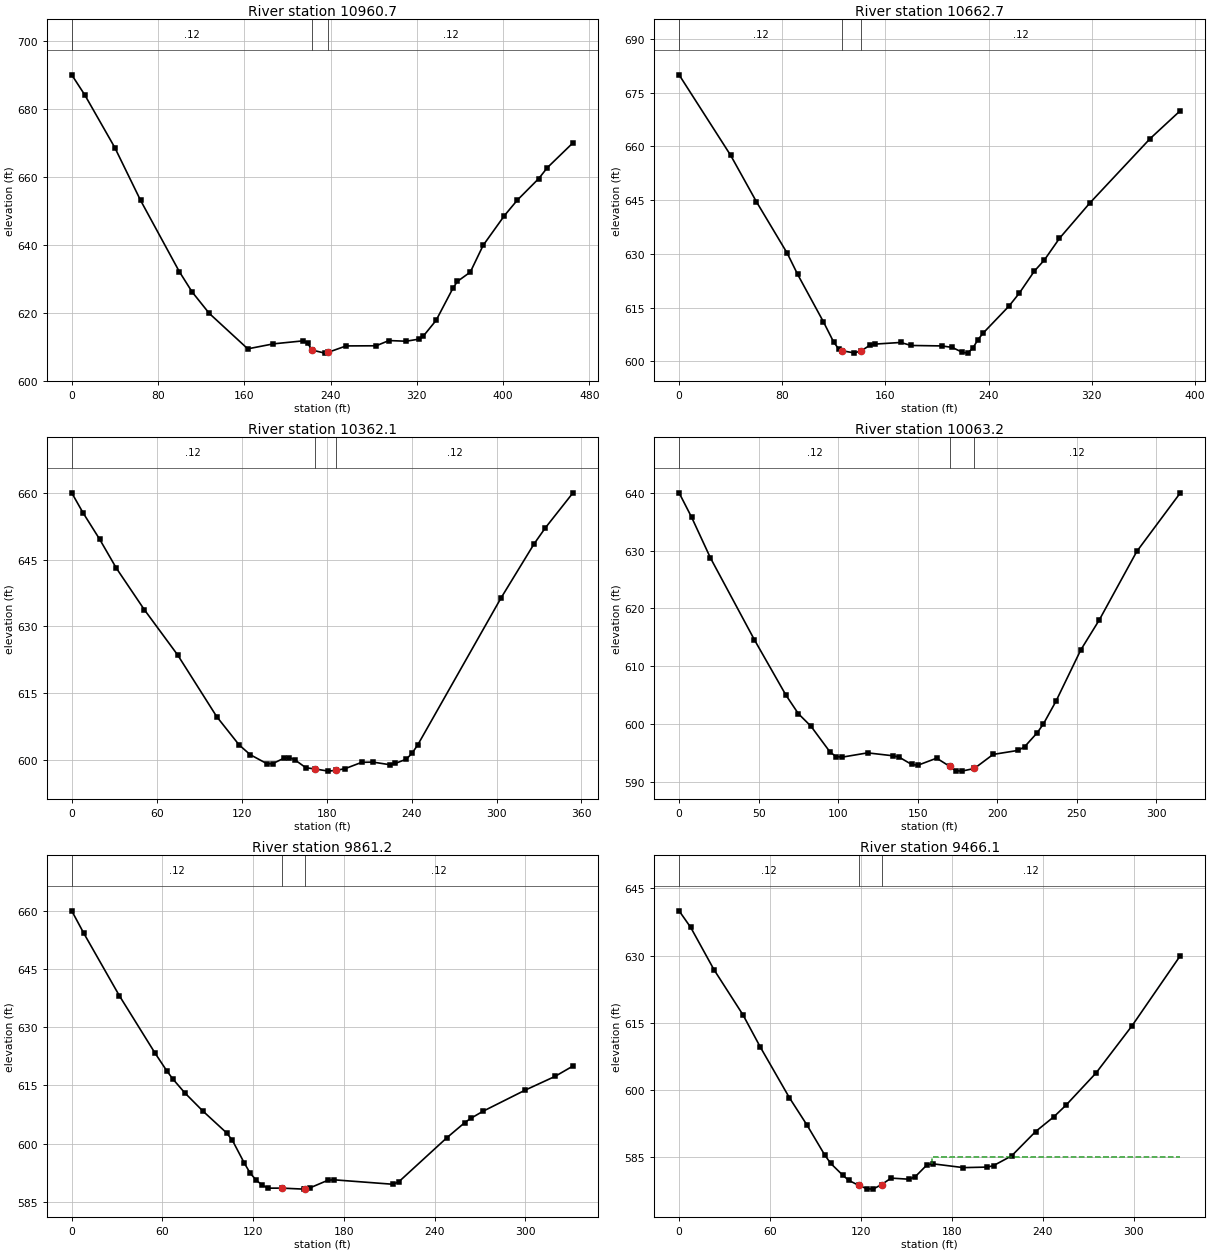
Type RM Length L Ch R = 1 ,10960.7 ,296,298,296.5
XS GIS Cut Line= 3
     2299505.002      405672.537     2299606.535      405651.436
     2299962.837      405709.421
#Sta/Elev= 30
       0     690      12  684.14    39.9  668.62    63.8  653.08    99.7  632.14
   111.6  626.14   127.5  619.83   163.2   609.4     187  610.87   214.8  611.76
   218.7     611     223  609.03   234.6  608.14     238  608.41   254.4  610.26
   282.2   610.3   294.1  611.84     310  611.64   321.9  612.26   325.8  613.09
   337.8  617.78   353.6  627.35   357.6  629.25   369.5  631.97   381.4  639.84
   401.2  648.62   413.1  653.15     433   659.5   440.9  662.69   464.7     670
#Mann= 3 ,-1 , 0
       0     .12       0     223    .045       0     238     .12       0
Bank Sta=223,238
XS Rating Curve= 0 ,0
Exp/Cntr=0.3,0.1

Type RM Length L Ch R = 1 ,10662.7 ,287.2,300.6,309
XS GIS Cut Line= 3
     2299559.184      405913.267     2299819.682      405954.034
     2299919.459      406029.192
#Sta/Elev= 30
       0     680      40  657.51    59.9   644.6    83.9  630.14    91.9  624.28
   111.9  611.03   119.8  605.41   123.8   603.4   126.1  602.97   135.8  602.35
   141.1  602.91   147.8  604.46   151.8  604.81   171.8  605.27   179.8  604.43
   203.7   604.3   211.7  603.89   219.7   602.5   223.7  602.29   227.7  603.68
   231.7  606.04   235.7  607.88   255.7   615.4   263.7  619.01   275.4  625.18
   283.2   628.3   294.9  634.35   318.3  644.16   365.2   662.2   388.6     670
#Mann= 3 ,-1 , 0
       0     .12       0   126.1    .045       0   141.1     .12       0
Bank Sta=126.1,141.1
XS Rating Curve= 0 ,0
Exp/Cntr=0.3,0.1

Type RM Length L Ch R = 1 ,10362.1 ,298.1,298.9,297.6
XS GIS Cut Line= 3
     2299507.505      406084.537      2299724.88      406219.772
     2299819.662      406244.537
#Sta/Elev= 30
       0     660     7.9  655.55    19.7  649.57    31.5  643.06    51.2  633.75
    74.8  623.54   102.4  609.66   118.2  603.31     126  601.12   137.8  599.09
   141.8  599.07   149.7   600.3   153.6  600.44   157.5  599.97   165.4  598.16
   171.7  597.91   181.2  597.41   186.7  597.59     193  597.96   204.8  599.39
   212.7  599.44   224.5  598.86   228.4  599.13   236.3   600.1   240.2  601.39
   244.2  603.22     303  636.26   326.5  648.51   334.4  652.09     354     660
#Mann= 3 ,-1 , 0
       0     .12       0   171.7    .045       0   186.7     .12       0
Bank Sta=171.7,186.7
XS Rating Curve= 0 ,0
Exp/Cntr=0.3,0.1

Type RM Length L Ch R = 1 ,10063.2 ,215,202,188.7
XS GIS Cut Line= 3
     2299373.461      406326.187     2299569.011      406445.435
     2299655.057      406444.537
#Sta/Elev= 30
       0     640     7.9  635.76    19.7  628.74    47.4  614.54    67.1  605.02
      75  601.77    82.9  599.61    94.8  595.18    98.7  594.34   102.7  594.27
   118.5     595   134.3   594.5   138.2  594.28   146.1  593.01   150.1  592.86
   161.9  594.08   170.1  592.67   173.8  591.92   177.7  591.84   185.6   592.3
   197.4  594.73   213.2  595.43   217.2  596.06   225.1  598.47     229     600
   236.9  603.93   252.5  612.81   264.2  618.03   287.7  629.85   315.1     640
#Mann= 3 ,-1 , 0
       0     .12       0   170.1    .045       0   185.6     .12       0
Bank Sta=170.1,185.6
XS Rating Curve= 0 ,0
Exp/Cntr=0.3,0.1

Type RM Length L Ch R = 1 ,9861.2  ,418.6,395.1,369.5
XS GIS Cut Line= 3
     2299308.823      406608.537     2299552.784      406600.537
     2299633.653      406566.999
#Sta/Elev= 30
       0     660     7.9  654.27    31.5  638.12    55.1  623.32      63  618.68
    66.9  616.64    74.8  613.07    86.6  608.44   102.4  602.77   106.3  600.82
   114.2  594.94   118.1  592.34     122  590.58     126  589.27   129.9   588.5
     139  588.51   153.5  588.25     154  588.29   157.5  588.56   169.3  590.51
   173.2  590.66   212.6   589.5   216.5  590.19   248.1  601.48     260   605.4
     264   606.5     272  608.31   299.8  613.74   319.7  617.31   331.6  619.99
#Mann= 3 ,-1 , 0
       0     .12       0     139    .045       0     154     .12       0
Bank Sta=139,154
XS Rating Curve= 0 ,0
Exp/Cntr=0.3,0.1

Type RM Length L Ch R = 1 ,9466.1  ,304.6,304.8,303.5
XS GIS Cut Line= 3
     2299644.114      406947.563     2299713.877       406893.62
     2299820.788      406675.863
#Sta/Elev= 30
       0     640     7.7  636.28      23  626.88    42.2  616.76    53.7  609.53
    72.8  598.28    84.4  592.19    96.1  585.51   100.1  583.61   108.1  580.96
     112  579.83   118.6  578.71     124  577.97     128  577.88   133.6  578.89
   139.9  580.34   151.8  580.09   155.8  580.64   163.7  583.33   167.7  583.52
   187.6  582.68   203.5   582.8   207.5  583.13   219.4  585.29   235.3  590.74
   247.3  594.02   255.2  596.57   275.1  603.78     299  614.38   330.8     630
#Mann= 3 ,-1 , 0
       0     .12       0   118.6    .045       0   133.6     .12       0
#XS Ineff= 2 , 0
                          166.99          585.05
Permanent Ineff=
       F       F
Bank Sta=118.6,133.6
XS Rating Curve= 0 ,0
Exp/Cntr=0.3,0.1

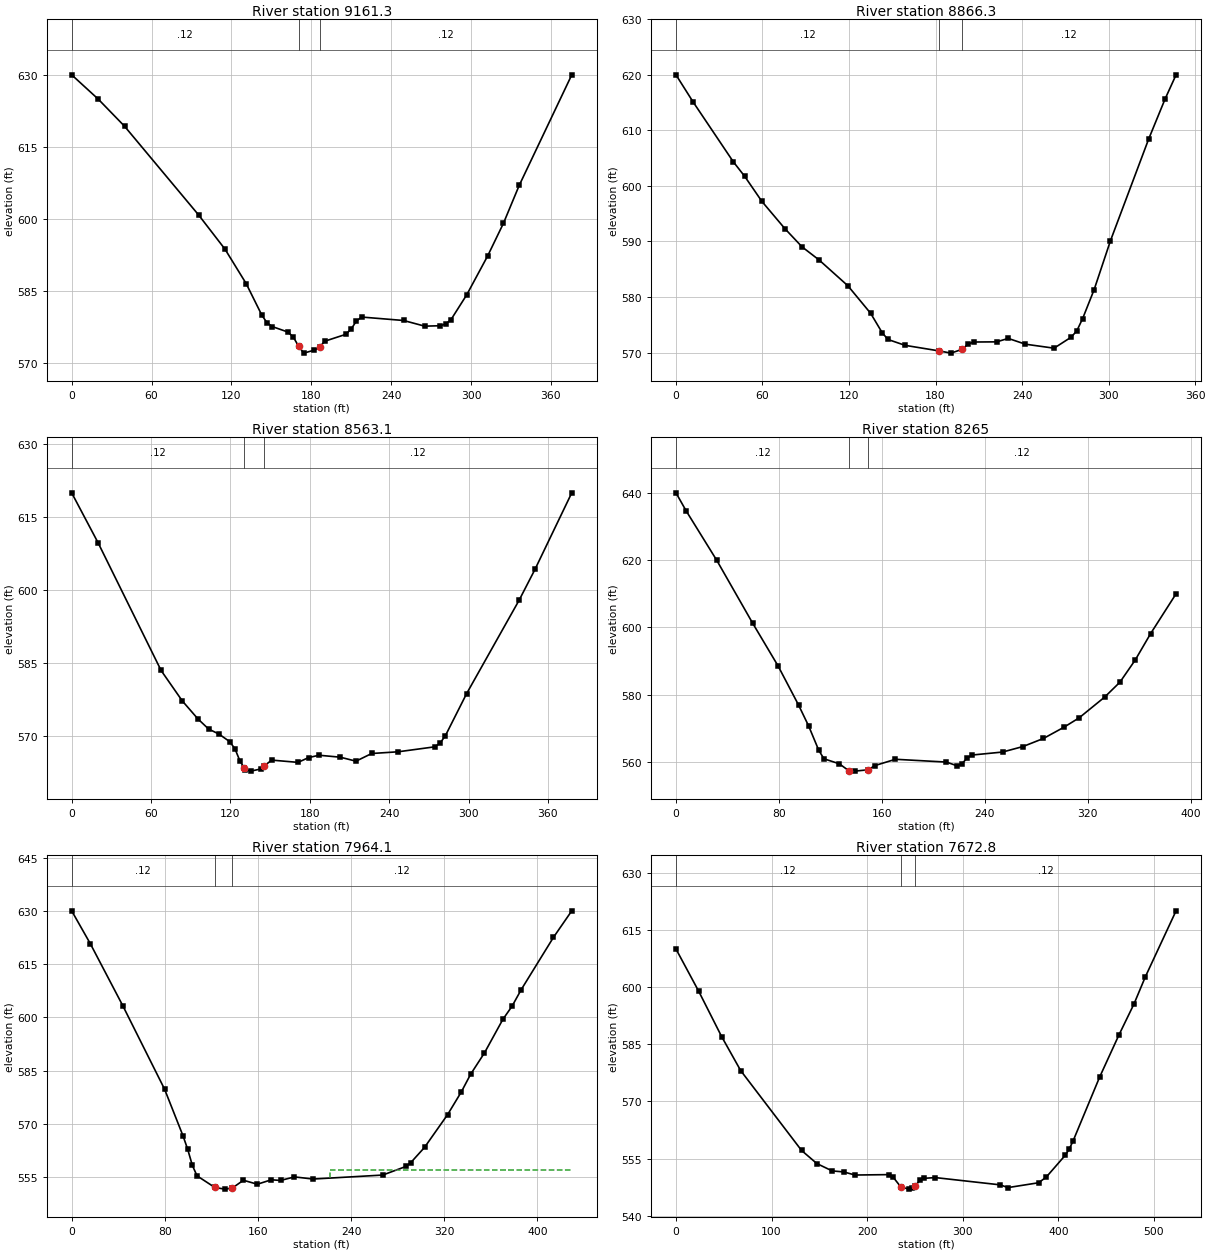
Type RM Length L Ch R = 1 ,9161.3  ,289.4,295,300.2
XS GIS Cut Line= 3
     2299890.695      407165.956     2299963.072      407066.301
       2300070.6      406837.835
#Sta/Elev= 30
       0     630    19.9  624.95    39.7  619.29    95.4  600.78   115.2  593.66
   131.1  586.49   142.9  579.89   146.8  578.31   150.8  577.52   162.6  576.38
   166.6   575.3   170.5  573.42   174.4     572   182.4  572.64   186.3   573.3
   190.2  574.49     206  575.92     210  577.04   213.9  578.68   217.8  579.52
   249.4   578.8   265.2  577.62     277  577.71     281  578.08   284.9  578.95
   296.8  584.16   312.5  592.25   324.4  599.08   336.2  606.95   375.7     630
#Mann= 3 ,-1 , 0
       0     .12       0   170.5    .045       0   186.3     .12       0
Bank Sta=170.5,186.3
XS Rating Curve= 0 ,0
Exp/Cntr=0.3,0.1

Type RM Length L Ch R = 1 ,8866.3  ,301.9,303.2,303.4
XS GIS Cut Line= 3
     2300119.065      407305.594     2300300.991      407079.805
     2300321.729      407026.923
#Sta/Elev= 30
       0     620    11.9  615.11    39.7  604.37    47.7  601.71    59.6  597.21
    75.5  592.32    87.4  589.04    99.3  586.66   119.2  582.03     135  577.07
     143  573.58     147  572.36   158.9   571.3   182.7  570.29   190.7   569.9
   198.6   570.6   202.6  571.55   206.6   571.9   222.4  571.93   230.4  572.55
   242.3  571.51   262.2  570.79   274.1  572.78     278  573.93     282  576.11
     290  581.34   301.3  590.13   327.8  608.44   339.2  615.66   346.8     620
#Mann= 3 ,-1 , 0
       0     .12       0   182.7    .045       0   198.6     .12       0
Bank Sta=182.7,198.6
XS Rating Curve= 0 ,0
Exp/Cntr=0.3,0.1

Type RM Length L Ch R = 1 ,8563.1  ,289.7,298.1,306.3
XS GIS Cut Line= 2
     2300384.156      407444.796     2300630.903       407158.37
#Sta/Elev= 30
       0     620    19.9  609.75    67.6  583.42    83.6  577.16    95.5  573.43
   103.5  571.37   111.4  570.32   119.4  568.78   123.4  567.31   127.3  564.72
   130.5  563.35   131.3  563.01   135.3   562.7   143.3  563.16   145.5  563.77
   151.2  564.97   171.1   564.5   179.1  565.49     187  565.97     203  565.57
   214.9  564.75   226.8  566.33   246.7  566.68   274.6  567.71   278.6  568.51
   282.5  570.01   298.5  578.65   338.3  597.94   350.2  604.24     378     620
#Mann= 3 ,-1 , 0
       0     .12       0   130.5    .045       0   145.5     .12       0
Bank Sta=130.5,145.5
XS Rating Curve= 0 ,0
Exp/Cntr=0.3,0.1

Type RM Length L Ch R = 1 ,8265    ,290.9,300.9,309.6
XS GIS Cut Line= 2
     2300550.383      407623.663     2300893.064      407440.537
#Sta/Elev= 30
       0     640     7.9  634.65    31.7  619.94    59.5  601.32    79.3  588.58
    95.2  576.98   103.1   570.7     111  563.44     115  560.97   126.9  559.49
   134.3  557.42   138.8  557.31   149.3   557.7   154.6  558.97   170.5  560.83
   210.1     560   218.1  558.93     222  559.46     226   561.1     230  562.09
   253.7  562.98   269.6  564.62   285.5  567.02   301.3  570.33   313.2  573.14
     333   579.3   344.9  583.74   356.8  590.34   368.7  598.15   388.5     610
#Mann= 3 ,-1 , 0
       0     .12       0   134.3    .045       0   149.3     .12       0
Bank Sta=134.3,149.3
XS Rating Curve= 0 ,0
Exp/Cntr=0.3,0.1

Type RM Length L Ch R = 1 ,7964.1  ,289,291.3,292.3
XS GIS Cut Line= 3
     2300640.606      407844.537     2300958.681      407820.184
     2301061.952      407780.537
#Sta/Elev= 30
       0     630      16  620.76    43.9  603.31    79.8  579.81    95.7  566.63
    99.7  562.85   103.7  558.33   107.7  555.42     123  552.14   131.6  551.68
     138  551.98   147.5  554.18   159.5  553.06   171.5  554.31   179.4  554.12
   191.4  555.12   207.4  554.52   267.2  555.64   287.1  558.06   291.1  559.06
   303.1  563.42     323  572.68   334.8  579.09   342.7     584   354.6  590.02
   370.4  599.45   378.3  603.16   386.2  607.84   413.8   622.5   429.6     630
#Mann= 3 ,-1 , 0
       0     .12       0     123    .045       0     138     .12       0
#XS Ineff= 2 , 0
                          221.59             557
Permanent Ineff=
       F       F
Bank Sta=123,138
XS Rating Curve= 0 ,0
Exp/Cntr=0.3,0.1

Type RM Length L Ch R = 1 ,7672.8  ,351.6,355.8,354.7
XS GIS Cut Line= 3
     2300614.052      408030.475     2300701.817      408117.251
     2301101.577         408114.
#Sta/Elev= 30
       0     610    23.9  598.85    47.8     587    67.7  578.09   131.4  557.13
   147.4  553.69   163.4  551.76   175.4   551.5   187.4  550.68   223.4  550.79
   227.4  550.06   235.1   547.6   243.4  546.98   247.4  547.16   250.1  547.84
   255.4  549.28   259.3  549.81   271.3  550.01   339.3   548.1   347.3  547.38
   379.3  548.65   387.3  550.11   407.3  555.87   411.3  557.43   415.3  559.53
   443.2  576.36   463.2  587.31   479.2  595.58   491.2  602.77   523.2  620.01
#Mann= 3 ,-1 , 0
       0     .12       0   235.1    .045       0   250.1     .12       0
Bank Sta=235.1,250.1
XS Rating Curve= 0 ,0
Exp/Cntr=0.3,0.1

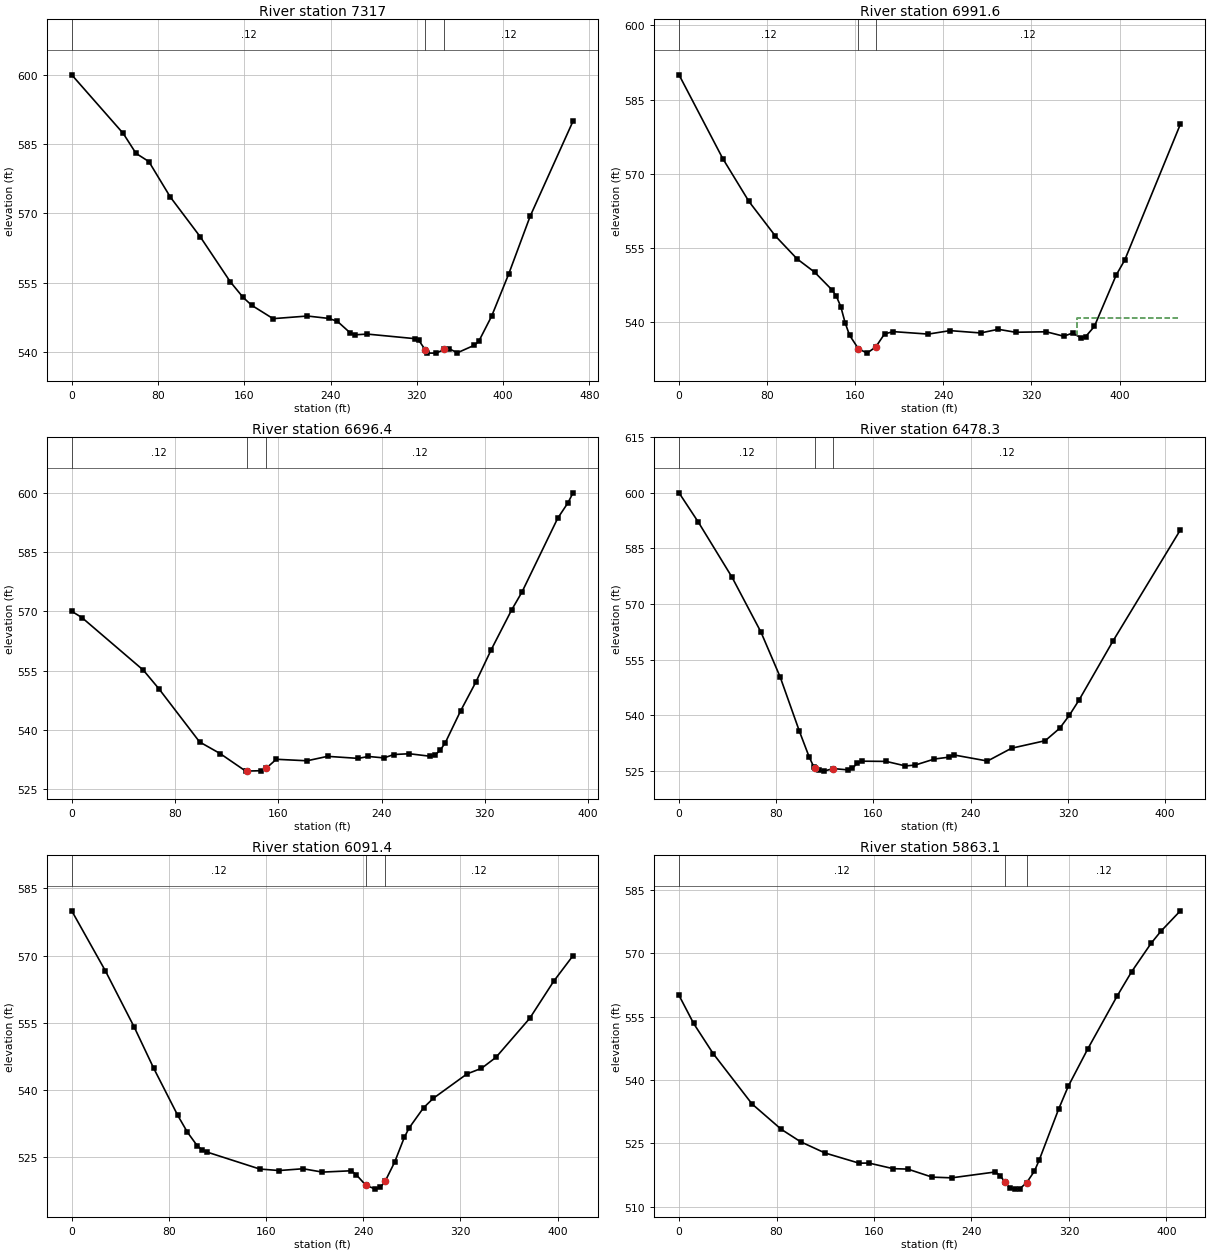
Type RM Length L Ch R = 1 ,7317    ,335.9,325.3,313
XS GIS Cut Line= 2
     2300482.865      408408.537      2300947.62      408409.032
#Sta/Elev= 30
       0     600    47.7  587.33    59.6     583    71.5  581.23    91.4  573.55
   119.2  564.93     147  555.21   158.9  551.83   166.8  550.13   186.7  547.23
   218.5   547.8   238.3  547.28   246.3  546.65   258.2  544.15   262.2  543.73
   274.1  543.89   317.8  542.91   321.8  542.53   327.9  540.44   329.7  539.78
   337.6  539.77   345.6  540.56   349.6  540.76   357.5  539.84   373.4  541.49
   377.4  542.33   389.3  547.76   405.2  556.93     425  569.38   464.8  589.99
#Mann= 3 ,-1 , 0
       0     .12       0   327.9    .045       0   345.6     .12       0
Bank Sta=327.9,345.6
XS Rating Curve= 0 ,0
Exp/Cntr=0.3,0.1

Type RM Length L Ch R = 1 ,6991.6  ,300.3,295.2,289
XS GIS Cut Line= 3
     2300576.114      408782.011     2300924.385      408591.543
     2300981.745      408581.477
#Sta/Elev= 30
       0     590    39.7  573.07    63.5  564.38    87.3  557.45   107.2  552.77
   123.1  550.09   138.9   546.5   142.9   545.2   146.9   543.1   150.8  539.86
   154.8  537.35   162.8  534.62   170.7  533.71   178.6  534.95   186.6  537.59
   194.5  538.06   226.3  537.56   246.1  538.26   273.9  537.79   289.8  538.53
   305.6  537.93   333.4  538.03   349.3  537.13   357.3  537.76   365.2  536.79
   369.2  537.05   377.1   539.1     397  549.52   404.7  552.53   455.2     580
#Mann= 3 ,-1 , 0
       0     .12       0   162.8    .045       0   178.6     .12       0
#XS Ineff= 2 , 0
                           361.5           540.8
Permanent Ineff=
       F       F
Bank Sta=162.8,178.6
XS Rating Curve= 0 ,0
Exp/Cntr=0.3,0.1

Type RM Length L Ch R = 1 ,6696.4  ,218.8,218.1,215.8
XS GIS Cut Line= 2
     2300843.132      408975.555     2301128.921      408712.537
#Sta/Elev= 30
       0     570     7.9  568.41    55.5  555.09    67.4  550.44    99.1  536.91
   114.9  533.99   134.8  529.53   135.8  529.54   146.6  529.64   150.8   530.3
   158.5  532.53   182.3  532.15   198.2  533.27   221.9  532.76   229.9  533.24
   241.8  532.88   249.7  533.74   261.6  533.93   277.4  533.31   281.4  533.58
   285.4   534.8   289.3  536.64   301.2  544.73   313.1  552.08     325  560.28
   340.8  570.34   348.8  574.86   376.5  593.56   384.4  597.44   388.4     600
#Mann= 3 ,-1 , 0
       0     .12       0   135.8    .045       0   150.8     .12       0
Bank Sta=135.8,150.8
XS Rating Curve= 0 ,0
Exp/Cntr=0.3,0.1

Type RM Length L Ch R = 1 ,6478.3  ,380.6,387,391.8
XS GIS Cut Line= 3
     2300984.114      409135.013     2301210.216      408906.949
     2301257.056      408828.537
#Sta/Elev= 30
       0     600    15.9  592.09    43.6  577.26    67.4  562.48    83.3   550.3
    99.1   535.7     107  528.89     111  526.05   112.1  525.81     115  525.19
   118.9     525   127.1  525.68   138.8  525.34   142.7  525.83   146.7  527.07
   150.7  527.68   170.5  527.62   186.3   526.4   194.3  526.63   210.1  528.26
     222  528.76     226  529.37   253.8  527.72   273.6  531.17   301.3   533.2
   313.2  536.54   321.2  540.06   329.1  544.13   356.9  559.97   412.5     590
#Mann= 3 ,-1 , 0
       0     .12       0   112.1    .045       0   127.1     .12       0
Bank Sta=112.1,127.1
XS Rating Curve= 0 ,0
Exp/Cntr=0.3,0.1

Type RM Length L Ch R = 1 ,6091.4  ,232.9,228.3,223.4
XS GIS Cut Line= 2
     2301172.725      409391.327      2301526.31      409178.341
#Sta/Elev= 30
       0     580    27.8  566.55    51.6  553.96    67.5  544.85    87.3  534.32
    95.3  530.55   103.2   527.6   107.2  526.63   111.1  526.16   154.8  522.35
   170.7  522.01   190.5  522.41   206.4  521.66   230.2  521.96   234.2   521.1
   242.1  518.75     250  517.86     254  518.23     258  519.57   265.9  523.89
   273.9  529.44   277.8  531.51   289.7  536.03   297.7  538.13   325.5  543.59
   337.4  544.83   349.3  547.28   377.1  555.99   396.9  564.29   412.8     570
#Mann= 3 ,-1 , 0
       0     .12       0   242.1    .045       0     258     .12       0
Bank Sta=242.1,258
XS Rating Curve= 0 ,0
Exp/Cntr=0.3,0.1

Type RM Length L Ch R = 1 ,5863.1  ,293.8,294.3,294.7
XS GIS Cut Line= 2
     2301308.258      409642.253     2301608.734      409361.289
#Sta/Elev= 30
       0     560      12  553.35      28  546.24    59.9  534.32    83.9  528.32
    99.8  525.37   119.8  522.72   147.8  520.31   155.8  520.34   175.7  519.01
   187.7  518.91   207.7  517.01   223.7  516.84   259.6  518.23   263.6  517.35
   267.6  515.75   271.6  514.41   275.6  514.17   279.6  514.27  285.15  515.65
   291.6   518.4   295.6  521.06   311.5  533.09   319.5  538.55   335.5  547.38
   359.4  559.78   371.4  565.59   387.4  572.32   395.4  575.16   411.4     580
#Mann= 3 ,-1 , 0
       0     .12       0   267.6    .045       0  285.15     .12       0
Bank Sta=267.6,285.15
XS Rating Curve= 0 ,0
Exp/Cntr=0.3,0.1

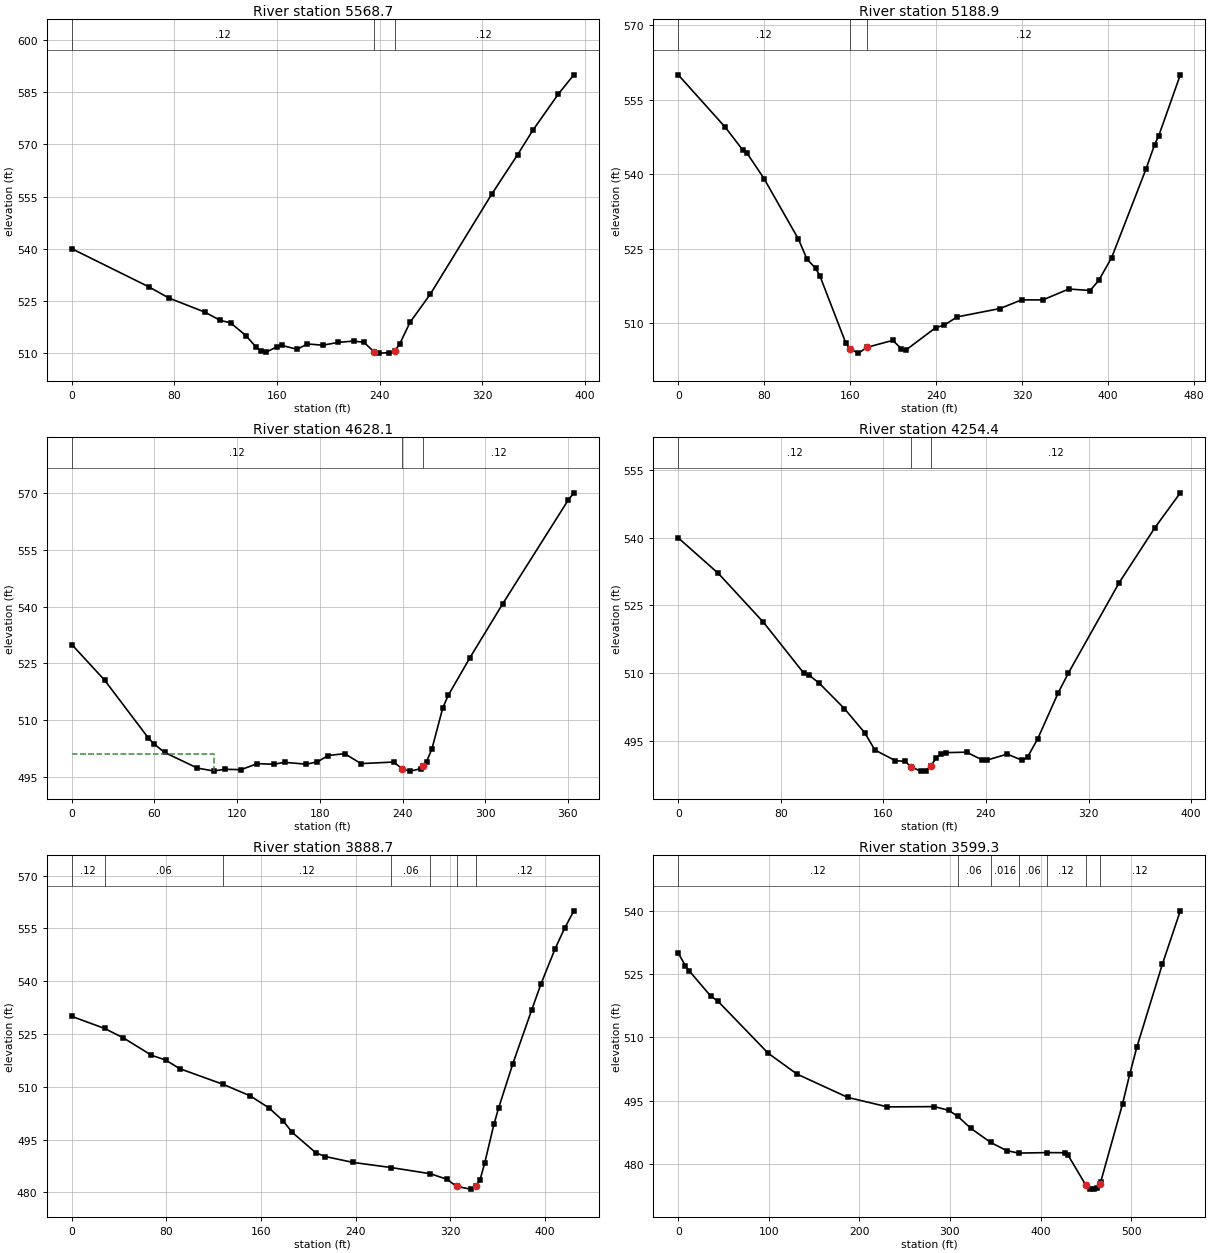
Type RM Length L Ch R = 1 ,5568.7  ,380,379.9,378.3
XS GIS Cut Line= 2
     2301523.646      409837.209     2301814.432      409575.228
#Sta/Elev= 30
       0     540    59.9  529.07    75.9  525.79   103.8  521.76   115.8  519.37
   123.8  518.69   135.8  514.99   143.8  511.66   147.8  510.58   151.8   510.3
   159.8  511.77   163.8  512.19   175.7  511.07   183.7  512.61   195.7  512.25
   207.7  513.07   219.7  513.43   227.6   513.1   235.6  510.41   239.6  509.97
   247.6  510.09   251.6  510.51   255.6  512.56   263.6  518.78   279.6  526.98
   327.5  555.76   347.5  567.01   359.4  574.04   379.4  584.53   391.4  590.01
#Mann= 3 ,-1 , 0
       0     .12       0   235.6    .045       0   251.6     .12       0
Bank Sta=235.6,251.6
XS Rating Curve= 0 ,0
Exp/Cntr=0.3,0.1

Type RM Length L Ch R = 1 ,5188.9  ,552.7,560.8,567.4
XS GIS Cut Line= 2
     2301736.114      410111.942     2302076.927      409792.537
#Sta/Elev= 30
       0     560    43.9  549.41    59.9  544.89    63.9  544.26    79.8  539.11
   111.8  526.92   119.8  522.88   127.8  521.05   131.7  519.56   155.7   506.1
   159.7  504.78   167.7  503.96   175.7  505.13   199.6  506.53   207.6  504.84
   211.6  504.54   239.5  509.09   247.5   509.6   259.5  511.26   299.4  512.94
   319.4  514.68   339.3  514.68   363.3  516.87   383.2  516.57   391.2   518.6
   403.2  523.18   435.2  541.04   443.1   545.9   447.1  547.77   467.1     560
#Mann= 3 ,-1 , 0
       0     .12       0   159.7    .045       0   175.7     .12       0
Bank Sta=159.7,175.7
XS Rating Curve= 0 ,0
Exp/Cntr=0.3,0.1

Type RM Length L Ch R = 1 ,4628.1  ,376.5,373.7,368.1
XS GIS Cut Line= 2
     2302107.342      410369.178     2302437.475      410215.177
#Sta/Elev= 30
       0  529.99    23.8   520.6    55.4  505.42    59.4  503.85    67.3  501.54
    91.1  497.41     103  496.63   110.9  497.09   122.8  496.98   134.6  498.58
   146.5  498.41   154.4  498.92   170.3  498.43   178.2  499.04   186.1  500.72
     198  501.21   209.9  498.58   233.6     499   239.9  497.16   245.5   496.6
   253.4  497.25   254.9  497.94   257.4  499.08   261.3  502.44   269.2  513.27
   273.2  516.62     289  526.56   312.8   540.8   360.3  568.12   364.3  569.99
#Mann= 3 ,-1 , 0
       0     .12       0   239.9    .045       0   254.9     .12       0
#XS Ineff= 2 , 0
          102.88   501.2
Permanent Ineff=
       F       F
Bank Sta=239.9,254.9
XS Rating Curve= 0 ,0
Exp/Cntr=0.3,0.1

Type RM Length L Ch R = 1 ,4254.4  ,362,365.7,367.4
XS GIS Cut Line= 3
     2302189.195      410619.457     2302270.083      410674.505
     2302512.114      410508.081
#Sta/Elev= 30
       0     540    31.3   532.1    66.5  521.24    97.8     510   101.8  509.55
   109.8  507.77   129.6  502.08   145.5   496.7   153.4  492.89   169.3  490.53
   177.2  490.35   181.2  489.19   189.1   488.2     193  488.29   197.1  489.36
     201  491.07     205  492.07     209  492.31   224.9  492.41   236.8  490.72
   240.7  490.64   256.6  491.98   268.5  490.58   272.5  491.35   280.4  495.39
   296.3  505.56   304.2  509.92   343.9  530.04   371.7  542.23   391.6     550
#Mann= 3 ,-1 , 0
       0     .12       0   181.2    .045       0   197.1     .12       0
Bank Sta=181.2,197.1
XS Rating Curve= 0 ,0
Exp/Cntr=0.3,0.1

Type RM Length L Ch R = 1 ,3888.7  ,285.5,289.4,293.1
XS GIS Cut Line= 2
     2302363.611      410881.041     2302737.754      410680.537
#Sta/Elev= 30
       0  530.01   27.73526.5793    43.6   523.9    67.4  518.96    79.3  517.61
    91.2  515.16  128.27510.6539   150.8  507.43   166.6  504.03   178.5  500.39
   186.4  497.04   206.3  491.26   214.2  490.19     238   488.5     270487.0539
  303.16485.2962   317.4   483.7   325.3  481.69   337.2  480.92  342.06  481.75
   345.1  483.45   349.1   488.3     357  499.43     361  504.09   372.9  516.54
   388.8  531.78   396.7  539.22   408.6  549.18   416.6     555   424.5     560
#Mann= 7 ,-1 , 0
       0     .12       0   27.73     .06       0  128.27     .12       0
     270     .06       0  303.16     .12       0   325.3    .045       0
  342.06     .12       0
Bank Sta=325.3,342.06
XS Rating Curve= 0 ,0
Exp/Cntr=0.3,0.1

Type RM Length L Ch R = 1 ,3599.3  ,185.1,185.1,185.1
XS GIS Cut Line= 3
     2302332.662      411061.085      2302473.96      411084.072
     2302864.114       410954.29
#Sta/Elev= 30
       0     530       8  526.94    11.9  525.83    35.8  519.82    43.7  518.62
    99.4  506.25   131.2  501.32   187.1  495.81     231  493.56   282.9  493.62
   298.8  492.73  308.81491.2882   322.8  488.52  344.85485.1499   362.7  483.19
  375.79482.6136  406.73482.7316   426.6   482.7   430.6  482.05   450.2  474.94
   454.5  474.13   458.5  474.08   462.5   474.4   465.2  475.38   466.5  475.85
   490.5  494.24   498.4  501.26   506.4  507.77   534.4   527.3   554.3     540
#Mann= 7 ,-1 , 0
       0     .12       0  308.81     .06       0  344.85    .016       0
  375.79     .06       0  406.73     .12       0   450.2    .045       0
   465.2     .12       0
Bank Sta=450.2,465.2
XS Rating Curve= 0 ,0
Exp/Cntr=0.3,0.1