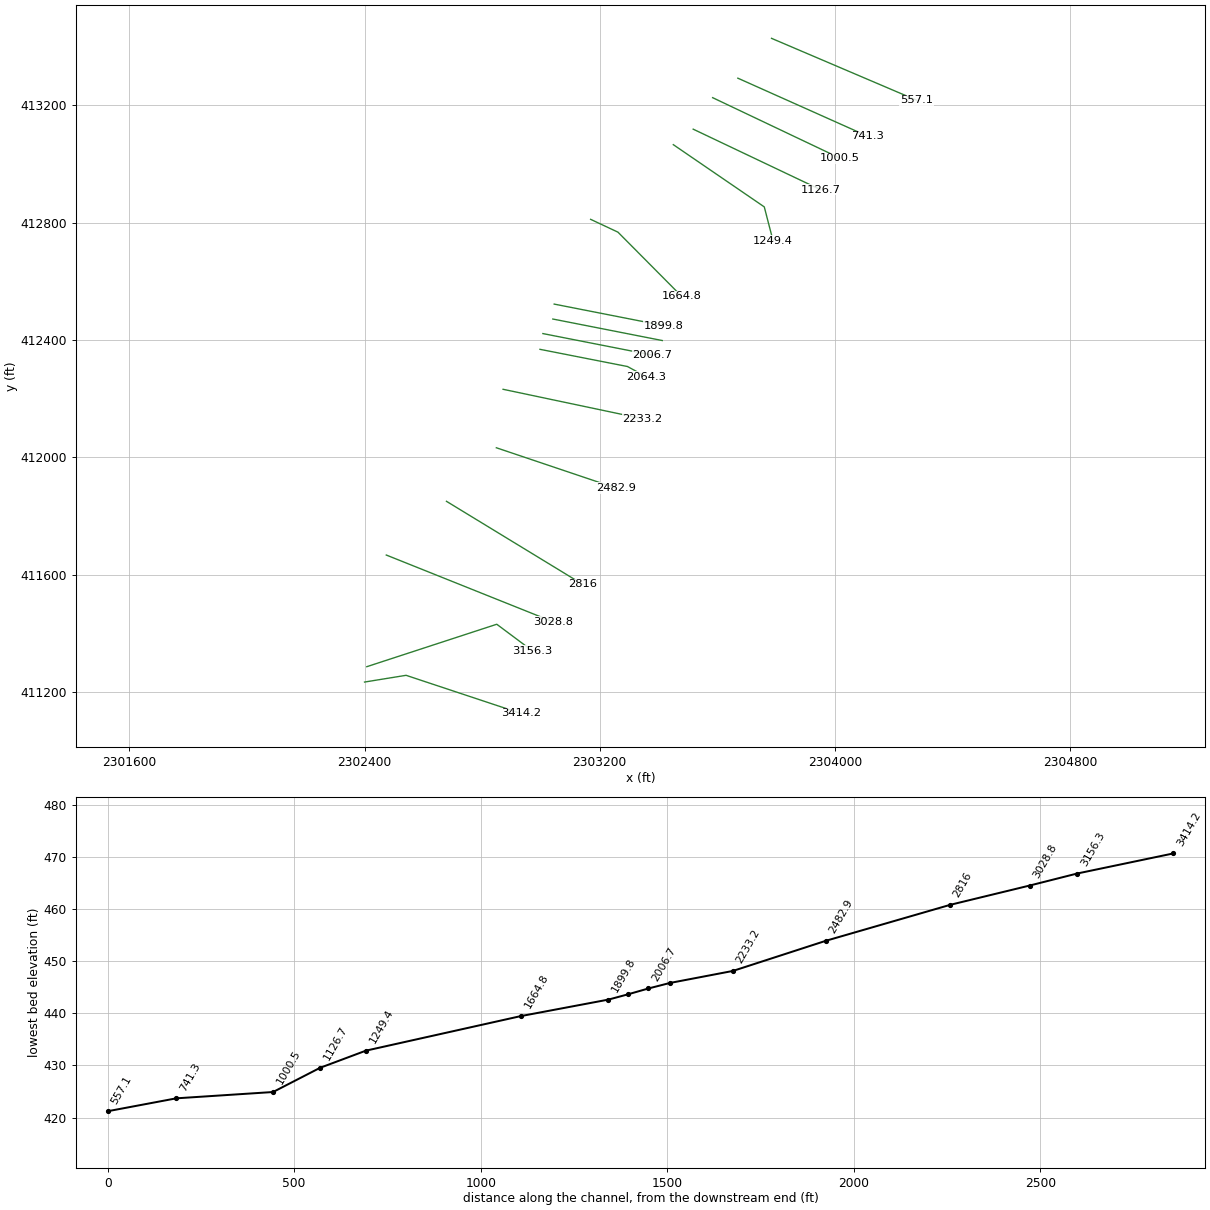
HEC-RAS study WILLETRUN.prj: WILLETRUN

--- WILLETRUN.g01 (geometry) --- (continued)

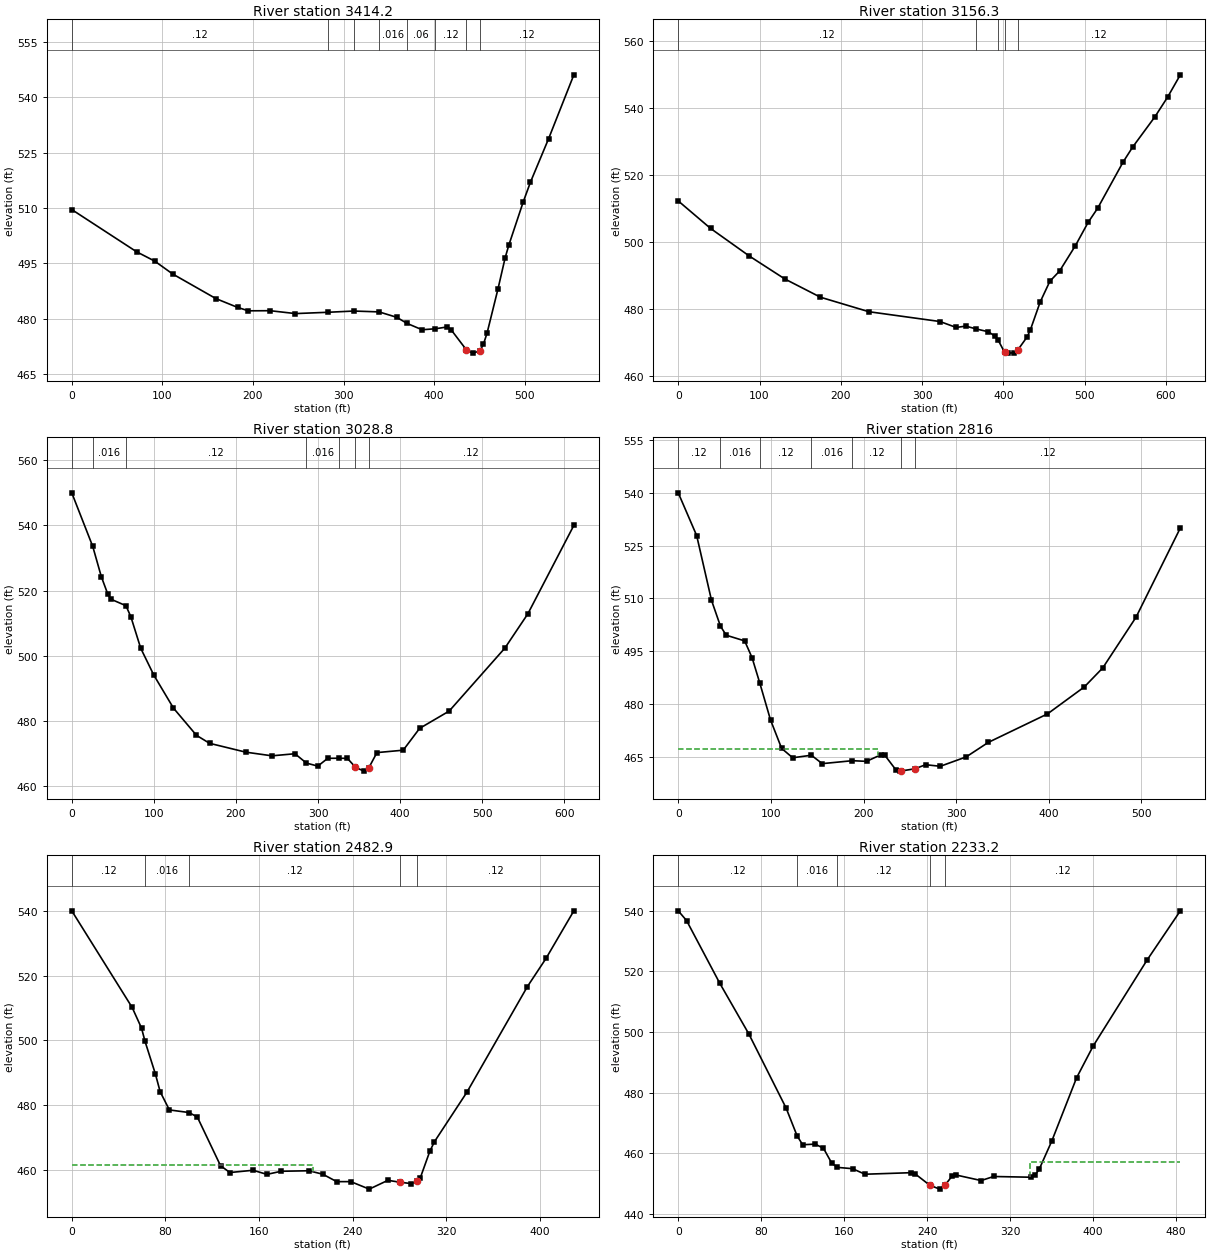
Type RM Length L Ch R = 1 ,3414.2  ,243.1,257.9,271.9
XS GIS Cut Line= 3
     2302399.936      411233.611     2302541.234      411256.598
     2302931.389      411126.816
#Sta/Elev= 30
       0  509.57    71.6  498.14    91.5  495.63   111.3  492.15   159.1  485.48
   183.1  483.09     195  482.17     219   482.2     247  481.42   282.6481.7733
  311.48482.1087  339.24481.8792   358.7  480.42  370.18478.7619   386.7  477.05
  401.51 477.311   414.6  477.81   418.6  477.11   435.6  471.63   442.6  470.72
   450.6  471.28   454.5  473.14   458.5  476.15   470.5  488.05   478.5  496.56
   482.5  499.93   498.4  511.63   506.4  516.99   526.4  528.73   554.3  546.03
#Mann= 8 ,-1 , 0
       0     .12       0   282.6     .06       0  311.48     .12       0
  339.24    .016       0  370.18     .06       0  401.51     .12       0
   435.6    .045       0   450.6     .12       0
Bank Sta=435.6,450.6
XS Rating Curve= 0 ,0
Exp/Cntr=0.3,0.1

Type RM Length L Ch R = 1 ,3156.3  ,143,127.5,111.5
XS GIS Cut Line= 3
     2302407.757      411286.028     2302849.924      411430.728
     2302972.114      411339.298
#Sta/Elev= 30
       0  512.33    39.8  504.11    87.5  495.86   131.2  489.01     175  483.56
   234.6  479.23   322.1   476.3     342  474.53   353.9  474.93  366.94474.0616
   381.7  473.24   389.7  471.92  393.77470.6831   401.6   467.1   405.6  466.86
   413.6  466.96   417.5   467.7   429.4  471.73   433.4  473.88   445.4  482.16
   457.3  488.33   469.2  491.37   488.7  498.96   504.4  505.93   516.1  510.15
   547.4  523.95   559.2  528.43   586.6  537.48   602.2  543.35   617.8     550
#Mann= 5 ,-1 , 0
       0     .12       0  366.94    .016       0  393.77     .12       0
   401.6    .045       0   417.5     .12       0
Bank Sta=401.6,417.5
XS Rating Curve= 0 ,0
Exp/Cntr=0.3,0.1

Type RM Length L Ch R = 1 ,3028.8  ,215.9,212.8,208.2
XS GIS Cut Line= 2
     2302473.916      411666.736     2303041.632       411439.02
#Sta/Elev= 30
       0  550.01   25.56 533.551      36  524.27      44  518.83      48  517.31
      66  515.35      72  511.95      84  502.29     100  494.02   123.9   483.9
   151.9  475.55   167.9  473.09   211.9  470.38   243.9  469.25   271.9  469.89
  285.93467.0127   299.8  466.09   311.8  468.48  325.21468.5129   335.8  468.47
  345.61  465.75   355.8  464.55  361.94  465.59   371.8  470.24   403.8  470.98
   423.8  477.68   459.8  482.99   527.7  502.34   555.7  512.87   611.7  540.01
#Mann= 7 ,-1 , 0
       0     .12       0   25.56    .016       0      66     .12       0
  285.93    .016       0  325.21     .12       0  345.61    .045       0
  361.94     .12       0
Bank Sta=345.61,361.94
XS Rating Curve= 0 ,0
Exp/Cntr=0.3,0.1

Type RM Length L Ch R = 1 ,2816    ,327.2,333.1,337.3
XS GIS Cut Line= 2
     2302678.732      411849.919     2303141.207      411567.444
#Sta/Elev= 30
       0  540.01    19.9  527.85    35.9  509.44   45.56502.0872    51.8  499.51
    71.7  497.89    79.7  493.11   88.05485.8786    99.6  475.41   111.6  467.32
   123.5  464.65  143.72 465.372   155.4  462.98  187.94463.8164   203.2  463.63
   219.2  465.56   223.1  465.32   235.1  461.15   239.1  460.85   240.4  460.88
   255.4  461.52     267  462.67   282.9  462.23   310.8   464.9   334.7  469.03
   398.5  477.12   438.3   484.8   458.2  490.21   494.1  504.63   541.9     530
#Mann= 7 ,-1 , 0
       0     .12       0   45.56    .016       0   88.05     .12       0
  143.72    .016       0  187.94     .12       0   240.4    .045       0
   255.4     .12       0
#XS Ineff= 2 , 0
          215.38  467.12
Permanent Ineff=
       F       F
Bank Sta=240.4,255.4
XS Rating Curve= 0 ,0
Exp/Cntr=0.3,0.1

Type RM Length L Ch R = 1 ,2482.9  ,246.4,249.7,251.6
XS GIS Cut Line= 2
     2302848.431      412032.537     2303254.949      411895.371
#Sta/Elev= 30
       0     540    51.6  510.12    59.6  503.74   62.57499.6711    71.5   489.5
    75.5  484.09    83.4  478.44  100.25477.6302   107.3  476.23   127.1   461.2
   135.1  459.08   154.9  459.78   166.8  458.51   178.8  459.47   202.6  459.63
   214.5  458.56   226.4  456.26   238.4  456.27   254.2  453.95   270.1  456.67
   280.4  456.09     290  455.66   295.4  456.48   297.9  457.54   305.9  465.62
   309.9  468.62   337.7  483.96   389.3  516.57   405.2  525.27     429     540
#Mann= 5 ,-1 , 0
       0     .12       0   62.57    .016       0  100.25     .12       0
   280.4    .045       0   295.4     .12       0
#XS Ineff= 2 , 0
          205.77  461.38
Permanent Ineff=
       F       F
Bank Sta=280.4,295.4
XS Rating Curve= 0 ,0
Exp/Cntr=0.3,0.1

Type RM Length L Ch R = 1 ,2233.2  ,166.9,168.9,169.2
XS GIS Cut Line= 2
     2302871.349      412231.883     2303344.873      412131.779
#Sta/Elev= 30
       0  540.03       8  536.83      40  516.14      68  499.42     104  474.91
  114.67465.6675     120   462.8     132  463.01     140  461.64     148  456.72
   153.4 455.329     168   454.9     180  453.07     224  453.57     228  453.29
   242.4  449.46     252  448.15   257.4  449.57     264  452.46     268   452.8
     292  450.98     304  452.32     340  452.08     344  452.78     348  454.74
     360  463.94     384   484.9     400   495.4     452   523.8     484  540.02
#Mann= 5 ,-1 , 0
       0     .12       0  114.67    .016       0   153.4     .12       0
   242.4    .045       0   257.4     .12       0
#XS Ineff= 2 , 0
                          339.46          456.95
Permanent Ineff=
       F       F
Bank Sta=242.4,257.4
XS Rating Curve= 0 ,0
Exp/Cntr=0.3,0.1

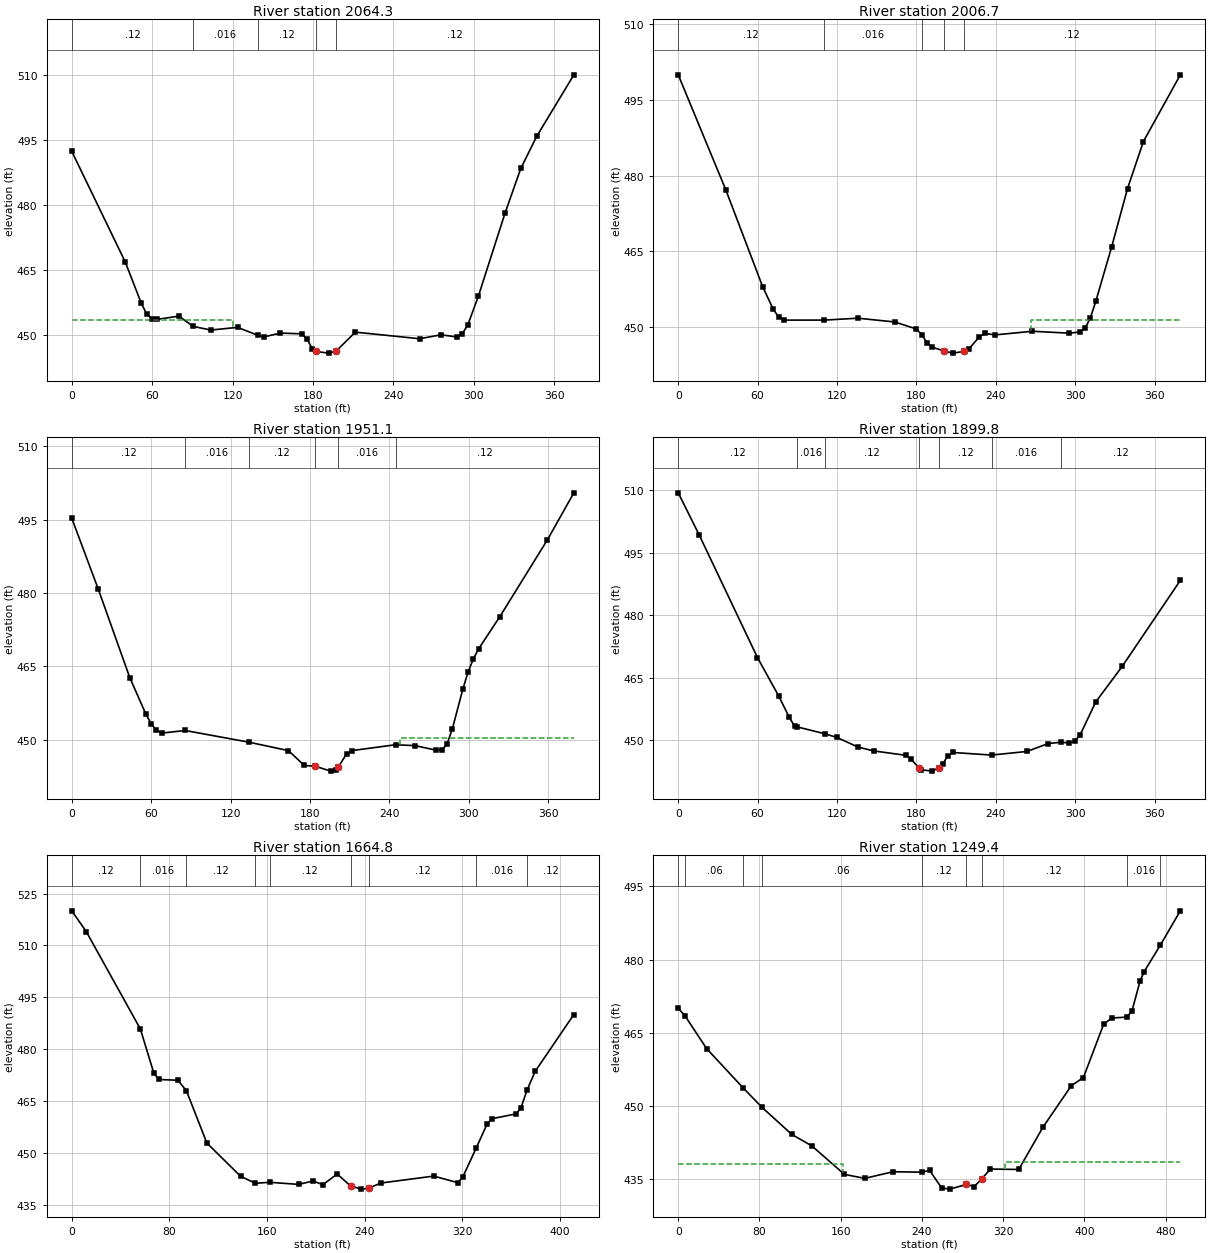
Type RM Length L Ch R = 1 ,2064.3  ,58.7,57.7,57.2
XS GIS Cut Line= 3
     2302996.907      412368.153     2303294.751      412309.517
     2303357.315      412275.336
#Sta/Elev= 30
       0  492.36    39.9  466.87    51.9  457.33    55.9  454.88    59.9  453.79
    63.9  453.62    79.9  454.37   90.76451.9922   103.8  451.16   123.8  451.78
  138.72449.9723   143.8  449.61   155.8  450.46   171.8  450.29   175.8     449
   179.7  446.75   182.3  446.22   191.7  445.84   197.3   446.3   211.7  450.68
   259.6  449.16   275.6  450.06   287.6  449.57   291.6  450.35   295.6  452.29
   303.6  459.04   323.4  478.09   335.2  488.42   347.1  495.83   374.8     510
#Mann= 5 ,-1 , 0
       0     .12       0   90.76    .016       0  138.72     .12       0
   182.3    .045       0   197.3     .12       0
#XS Ineff= 2 , 0
          120.07  453.56
Permanent Ineff=
       F       F
Bank Sta=182.3,197.3
XS Rating Curve= 0 ,0
Exp/Cntr=0.3,0.1

Type RM Length L Ch R = 1 ,2006.7  ,55.8,55.6,55.6
XS GIS Cut Line= 2
     2303006.805      412421.846     2303379.177      412348.537
#Sta/Elev= 30
       0     500      36  477.15    63.9   457.9    71.9  453.45    75.9  451.93
    79.9  451.33  110.48451.3322   135.8  451.71   163.8  450.96   179.8  449.58
  184.29448.4144   187.8  446.87   191.8  445.98   200.9   445.2   207.7  444.78
   215.9  445.12   219.7  445.62   227.7  448.03   231.7  448.68   239.7   448.4
   267.7  449.12   295.6  448.74   303.6  448.97   307.6  449.73   311.6  451.84
   315.6  455.04   327.6  465.86   339.6  477.44   351.6  486.76   379.5     500
#Mann= 5 ,-1 , 0
       0     .12       0  110.48    .016       0  184.29     .12       0
   200.9    .045       0   215.9     .12       0
#XS Ineff= 2 , 0
                          266.82          451.33
Permanent Ineff=
       F       F
Bank Sta=200.9,215.9
XS Rating Curve= 0 ,0
Exp/Cntr=0.3,0.1

Type RM Length L Ch R = 1 ,1951.1  ,51.3,51.3,51.2
XS GIS Cut Line= 2
     2303040.719       412471.46     2303413.091       412398.15
#Sta/Elev= 30
       0  495.27      20  480.81    43.9  462.69    55.9  455.35    59.9  453.34
    63.9  452.01    67.9   451.4    85.7451.9345  134.22449.5313   163.8  447.82
   175.8  444.79   183.8  444.66   195.8  443.64   199.8  443.93  201.52  444.51
   207.7  447.14   211.7  447.83  244.74449.0238   259.7  448.84   275.6   447.9
   279.6  447.94   283.6  449.14   287.6   452.2   295.6  460.39   299.6  463.91
   303.6  466.58   307.6  468.64   323.6  475.19   359.5  490.85   379.5  500.45
#Mann= 6 ,-1 , 0
       0     .12       0    85.7    .016       0  134.22     .12       0
   183.8    .045       0  201.52    .016       0  244.74     .12       0
#XS Ineff= 2 , 0
                          247.82          450.41
Permanent Ineff=
       F       F
Bank Sta=183.8,201.52
XS Rating Curve= 0 ,0
Exp/Cntr=0.3,0.1

Type RM Length L Ch R = 1 ,1899.8  ,248.2,235,221.3
XS GIS Cut Line= 2
     2303045.296      412522.373     2303417.668      412449.064
#Sta/Elev= 30
       0  509.38      16  499.17    59.9  469.87    75.9  460.68    83.9  455.57
    87.9  453.45   90.04 453.252  111.16451.5717   119.8  450.74   135.8  448.43
   147.8  447.49   171.8  446.46   175.8  445.57   182.3  443.34   183.8  442.97
   191.8  442.65   197.3   443.5   199.8  444.28   203.7  446.28   207.7  447.12
  236.84   446.5   263.7  447.37   279.6  449.27  289.01449.5653   295.6  449.42
   299.6  449.79   303.6  451.23   315.6  459.25   335.6  467.78   379.5  488.38
#Mann= 7 ,-1 , 0
       0     .12       0   90.04    .016       0  111.16     .12       0
   182.3    .045       0   197.3     .12       0  236.84    .016       0
  289.01     .12       0
Bank Sta=182.3,197.3
XS Rating Curve= 0 ,0
Exp/Cntr=0.3,0.1

Type RM Length L Ch R = 1 ,1664.8  ,410.7,415.4,419.2
XS GIS Cut Line= 3
      2303169.25      412811.401     2303262.285      412767.659
     2303479.474      412548.467
#Sta/Elev= 30
       0     520    11.9  513.98   56.21485.8104    67.2   473.1    71.2  471.21
      87  470.97   93.97467.9156   110.7  452.81   138.4  443.18  150.38  441.18
  162.31441.4492   185.9  440.85   197.8  441.83   205.7  440.75   217.5  443.85
   228.5  440.37   237.3  439.48   243.5  439.76   253.1  441.24   296.6  443.25
   316.4  441.34   320.4     443  331.26451.2654   340.2  458.24   344.1  459.84
   363.9  461.24   367.9  462.85  373.08468.1408   379.7  473.55   411.4     490
#Mann= 9 ,-1 , 0
       0     .12       0   56.21    .016       0   93.97     .12       0
  150.38     .06       0  162.31     .12       0   228.5    .045       0
   243.5     .12       0  331.26    .016       0  373.08     .12       0
Bank Sta=228.5,243.5
XS Rating Curve= 0 ,0
Exp/Cntr=0.3,0.1

Type RM Length L Ch R = 1 ,1249.4  ,119.2,122.7,126.3
XS GIS Cut Line= 3
     2303450.662       413065.99     2303760.114      412853.856
     2303789.984      412738.407
#Sta/Elev= 30
       0  470.01    7.04468.3088    27.9  461.72   64.25453.5519    82.5449.6405
   111.8  444.08   131.7   441.7   163.6  435.87   183.6  435.05   211.5  436.41
   240.2436.3203   247.5   436.7   259.4  433.08   267.4  432.84   283.7   433.8
   291.4  433.37   298.7  434.88   307.3  436.96   335.3  436.88   359.2  445.58
   387.1  454.09     399  455.76   418.9  466.71   426.9  467.98  441.57468.1677
   446.7  469.35   454.7  475.53   458.7  477.48  474.78482.9731   494.4     490
#Mann= 9 ,-1 , 0
       0     .08       0    7.04     .06       0   64.25     .08       0
    82.5     .06       0   240.2     .12       0   283.7    .045       0
   298.7     .12       0  441.57    .016       0  474.78     .12       0
#XS Ineff= 2 , 0
          162.52  438.02  321.93          438.33
Permanent Ineff=
       F       F
Bank Sta=283.7,298.7
XS Rating Curve= 0 ,0
Exp/Cntr=0.3,0.1

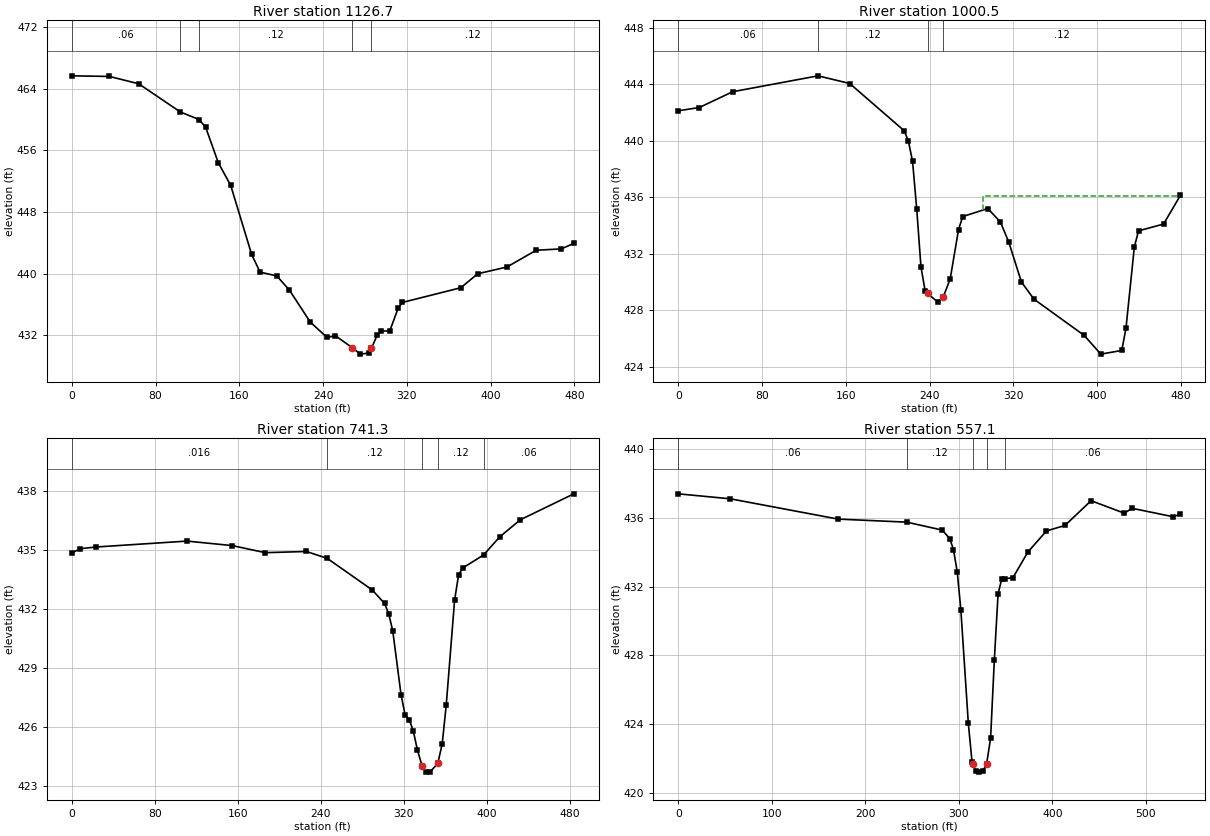
Type RM Length L Ch R = 1 ,1126.7  ,125.8,126.1,127.2
XS GIS Cut Line= 2
      2303518.25      413118.849     2303951.193      412912.685
#Sta/Elev= 30
       0  465.68      36   465.6    63.9  464.65  103.82 460.975  121.54460.0083
   127.9  458.99   139.9  454.41   151.8  451.45   171.8  442.49   179.8   440.2
   195.8   439.7   207.8  437.87   227.8  433.71   243.8  431.71   251.8  431.94
   267.9  430.38   275.7  429.55   283.7  429.69  286.16   430.3   291.7  432.02
   295.7  432.55   303.7  432.56   311.7  435.51   315.7  436.26   371.6  438.17
   387.6  439.98   415.6  440.86   443.6  443.04   467.5  443.21   479.5  443.93
#Mann= 5 ,-1 , 0
       0     .06       0  103.82     .08       0  121.54     .12       0
   267.9    .045       0  286.16     .12       0
Bank Sta=267.9,286.16
XS Rating Curve= 0 ,0
Exp/Cntr=0.3,0.1

Type RM Length L Ch R = 1 ,1000.5  ,255.7,259.2,258
XS GIS Cut Line= 2
     2303584.439      413226.271     2304017.382      413020.107
#Sta/Elev= 30
       0  442.11      20  442.34      52  443.46  133.54444.5841   163.8  444.04
   215.8   440.7   219.8  439.97   223.8  438.53   227.8  435.13   231.8  431.08
   235.8  429.37   238.1  429.19   247.8  428.59   253.1  428.95   259.7  430.21
   267.7  433.71   271.7  434.63   295.7   435.2   307.7  434.24   315.7  432.82
   327.7  430.01   339.7  428.79   387.6  426.23   403.6   424.9   423.6  425.16
   427.6  426.73   435.6  432.48   439.6  433.62   463.5   434.1   479.5  436.12
#Mann= 4 ,-1 , 0
       0     .06       0  133.54     .12       0   238.1    .045       0
   253.1     .12       0
#XS Ineff= 2 , 0
                          291.41          436.09
Permanent Ineff=
       F       F
Bank Sta=238.1,253.1
XS Rating Curve= 0 ,0
Exp/Cntr=0.3,0.1

Type RM Length L Ch R = 1 ,741.3   ,183.6,184.2,184.5
XS GIS Cut Line= 2
      2303670.22      413292.717     2304112.061      413094.801
#Sta/Elev= 30
       0  434.86     7.9  435.08    23.8  435.17   111.1  435.47   154.8  435.24
   186.5  434.88   226.2  434.94  246.26434.5903   289.7  432.98   301.6  432.29
   305.6  431.76   309.5  430.89   317.5  427.63   321.4  426.61   325.4  426.37
   329.4  425.77   333.3  424.81   337.9  423.99   341.3   423.7   345.2  423.69
   352.9  424.13   357.2  425.14   361.1  427.13   369.1  432.45     373  433.76
     377   434.1  397.02 434.761   412.7  435.69   432.6  436.56   484.1  437.88
#Mann= 5 ,-1 , 0
       0    .016       0  246.26     .12       0   337.9    .045       0
   352.9     .12       0  397.02     .06       0
Bank Sta=337.9,352.9
XS Rating Curve= 0 ,0
Exp/Cntr=0.3,0.1

Type RM Length L Ch R = 1 ,557.1   ,561.5,557.1,552.1
XS GIS Cut Line= 2
     2303784.804      413428.568     2304278.293       413217.63
#Sta/Elev= 30
       0   437.4    55.7  437.11   170.9  435.93  244.26435.7524   282.2  435.29
   290.2   434.8   294.2  434.16   298.2  432.88   302.1  430.66   310.1  424.05
   314.1  421.78   314.7   421.7     318  421.25     322  421.21     326  421.29
   329.7  421.71   333.9  423.18   337.9  427.74   341.9  431.58   345.9  432.47
  349.24432.4614   357.8  432.52   373.7  434.01   393.6  435.24   413.4  435.56
   441.3     437     477  436.27     485  436.56   528.7  436.07   536.7   436.2
#Mann= 5 ,-1 , 0
       0     .06       0  244.26     .12       0   314.7    .045       0
   329.7     .12       0  349.24     .06       0
Bank Sta=314.7,329.7
XS Rating Curve= 0 ,0
Exp/Cntr=0.3,0.1

Chan Stop Cuts=-1
Use User Specified Reach Order=0
Composite Channel Slope=5